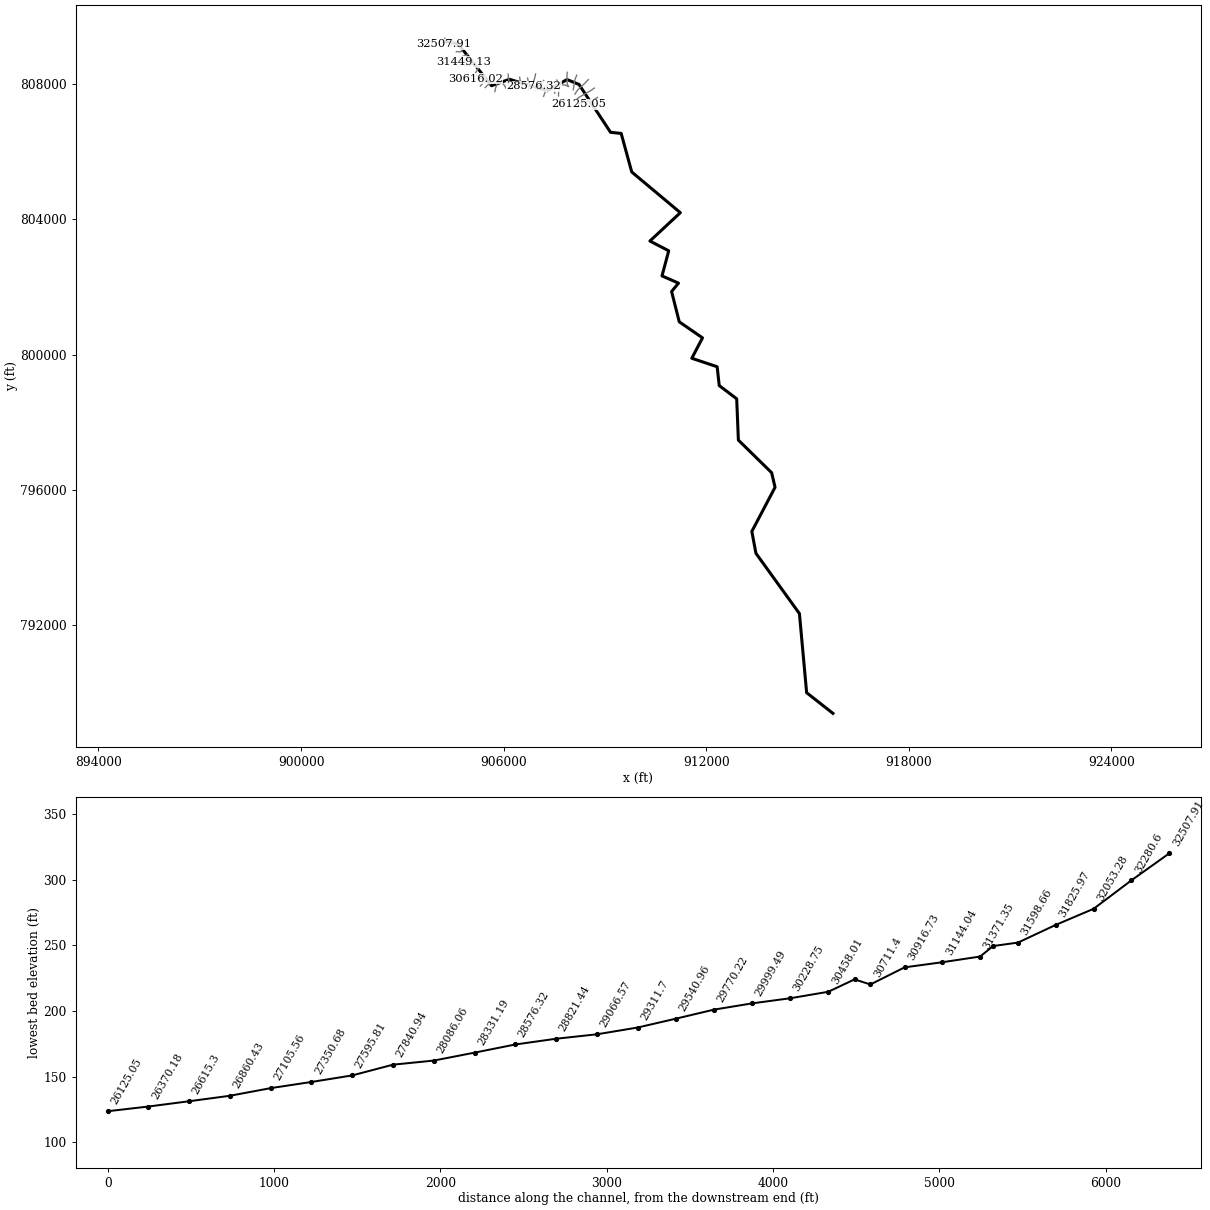
--- 13117_ras.prj (project) ---

Proj Title=13117
Current Plan=p01
Default Exp/Contr=0.3,0.1
English Units
Geom File=g01
Flow File=f01
Plan File=p01
Y Axis Title=Elevation
X Axis Title(PF)=Main Channel Distance
X Axis Title(XS)=Station
BEGIN DESCRIPTION:
RFD model 13117 exported to HEC-RAS
END DESCRIPTION:

--- 13117_ras.p01 (plan) ---

Plan Title=Plan 01
Program Version=4.10
Short Identifier=Plan 01
Geom File=g01
Flow File=f01
Subcritical Flow
Calc Critical at every XS
Secant Critical Depth

--- 13117_ras.f01 (steady flow) ---

Flow Title=Flow 01
Program Version=5.01
Number of Profiles= 6
Profile Names=10yr,25yr,50yr,100yr,100plus,500yr
River Rch & RM=13117,76,32507.91
  211.12   307.8  391.11  457.44  667.86 1022.31
River Rch & RM=13117,76,31598.66
  263.68  385.34  490.47  574.35  838.56 1246.07
River Rch & RM=13117,76,31449.13
  272.31  398.14  506.95   593.8  866.95 1282.94
River Rch & RM=13117,76,31371.35
  274.97   402.1  512.05  599.84  875.76 1294.38
River Rch & RM=13117,76,31144.04
  279.75  409.21   521.2  610.66  891.57 1314.87
River Rch & RM=13117,76,30916.73
   370.1  543.05  693.24  813.55 1187.79 1687.78
River Rch & RM=13117,76, 30711.4
  377.57  554.16  707.58  830.51 1212.55 1718.53
River Rch & RM=13117,76,30616.02
  386.13  567.06  724.34  850.46 1241.67 1755.15
River Rch & RM=13117,76,30458.01
  388.04  569.93  728.06  854.89 1248.14 1763.25
River Rch & RM=13117,76,30228.75
  393.71  578.47  739.16   868.1 1267.43 1787.45
River Rch & RM=13117,76,29999.49
  405.69  596.62  762.83  896.38 1308.72 1839.45
River Rch & RM=13117,76,29770.22
  413.83   608.8   778.6  915.09 1336.03 1873.15
River Rch & RM=13117,76,29540.96
  433.58  638.46  817.06   960.8 1402.76 1955.39
River Rch & RM=13117,76, 29311.7
  443.71  653.92  837.32  985.08 1438.22 1999.86
River Rch & RM=13117,76,29066.57
  459.16  677.43  868.08 1021.93 1492.01 2066.79
River Rch & RM=13117,76,28821.44
  468.71  692.02  887.19 1044.85 1525.49 2108.43
River Rch & RM=13117,76,28576.32
  517.54  765.28  982.17 1157.68 1690.22 2306.56
River Rch & RM=13117,76,28331.19
  533.35  789.35 1013.67  1195.4 1745.29 2373.51
River Rch & RM=13117,76,28086.06
   546.2  809.03 1039.55 1226.52 1790.71 2429.05
River Rch & RM=13117,76,27840.94
  551.55  817.25 1050.34  1239.5 1809.68 2452.19
River Rch & RM=13117,76,27595.81
  553.58  820.37 1054.47 1244.47 1816.93 2461.06
River Rch & RM=13117,76,27350.68
  557.97  827.16 1063.44 1255.31 1832.75 2480.55
River Rch & RM=13117,76,27105.56
  602.81  894.48 1150.78 1359.11 1984.29 2658.48
River Rch & RM=13117,76,26860.43
  626.37  930.17 1197.35 1414.72 2065.49 2754.19
River Rch & RM=13117,76, 26615.3
  874.08 1301.42 1678.58 1985.92 2899.44 3694.76
River Rch & RM=13117,76,26370.18
  877.69 1307.02    1686 1994.89 2912.53 3709.87
River Rch & RM=13117,76,26125.05
  903.22 1346.43 1738.06 2057.72 3004.27 3814.99
River Rch & RM=13117,76, 25575.5
  940.25 1403.54 1813.46 2148.68 3137.07 3966.16
River Rch & RM=13117,76,25039.95
 1266.19 1896.13 2455.66 2914.48 4255.15 5170.63
River Rch & RM=13117,76,24766.09
  1276.9 1912.86 2477.95 2941.56 4294.68 5214.29
River Rch & RM=13117,76,24321.74
 1326.77 1990.29 2580.64 3065.89 4476.19 5412.31
River Rch & RM=13117,76,23959.26
  1359.1 2040.98 2648.28 3148.21 4596.39 5544.47
River Rch & RM=13117,76,23848.08
 1368.18 2055.39 2667.66 3171.95 4631.05  5583.1
River Rch & RM=13117,76,23625.48
 1493.48 2252.07 2930.32 3491.88 5098.14 6092.42
River Rch & RM=13117,76,23386.53
 1511.87 2281.23 2969.52 3539.89 5168.24 6169.28
River Rch & RM=13117,76,23122.53
 1532.64 2314.55 3014.62 3595.46 5249.37  6259.3
River Rch & RM=13117,76,22819.53
 1534.71 2317.83 3019.02 3600.85 5257.25  6267.9
River Rch & RM=13117,76,22607.91
 1546.18 2336.31  3044.1 3631.82 5302.46 6318.21
River Rch & RM=13117,76,22351.39
 1591.74 2408.53 3141.14 3750.66 5475.96    6507
River Rch & RM=13117,76, 22007.2
  1594.5 2412.98 3147.19 3758.13 5486.86  6519.1
River Rch & RM=13117,76,21685.41
 1610.62 2438.92 3182.37 3801.55 5550.26 6589.14
River Rch & RM=13117,76,21243.44
 1619.59  2453.3 3201.83 3825.54 5585.29 6627.66
River Rch & RM=13117,76,20628.87
 1793.92 2725.46 3564.26 4265.82  6228.1 7304.47
River Rch & RM=13117,76,20153.35
 1795.85 2728.54 3568.43 4270.96 6235.59 7312.57
River Rch & RM=13117,76, 19618.2
 1814.89 2759.25 3610.15 4322.53 6310.89 7394.52
River Rch & RM=13117,76,18986.99
 1818.35 2764.85 3617.76 4331.94 6324.63 7409.48
River Rch & RM=13117,76,18564.78
  1838.6 2797.41 3661.92 4386.44 6404.21 7495.59
River Rch & RM=13117,76,   18168
 1881.64 2866.86 3756.31 4503.16 6574.61 7680.28
River Rch & RM=13117,76,17621.26
 1886.17 2874.15  3766.2 4515.39 6592.46 7699.56
River Rch & RM=13117,76,17277.72
 1887.77 2876.73  3769.7  4519.7 6598.77 7706.36
River Rch & RM=13117,76,16989.72
 1938.12 2957.48 3879.05  4654.5 6795.57 7917.14
River Rch & RM=13117,76,16522.25
 1943.11 2965.53 3889.99 4668.04 6815.34 7938.43
River Rch & RM=13117,76,16054.78
 1986.93 3035.95 3985.47 4785.88 6987.39  8122.4
River Rch & RM=13117,76,15587.31
 3846.89 5938.34 7852.49 9482.67 13844.714785.57
River Rch & RM=13117,76,15106.31
 3863.33 5964.93 7888.74 9527.5813910.2714849.56
River Rch & RM=13117,76,14670.34
 3923.73 6062.76 8022.18 9693.0114151.7915085.29
River Rch & RM=13117,76,13931.46
 3965.65 6130.66  8114.8 9807.8314319.4415248.58
River Rch & RM=13117,76,13468.17
 3975.16 6146.09 8135.87 9833.9914357.6215285.83
River Rch & RM=13117,76,13004.88
 3996.92 6181.56 8184.45 9894.4214445.8515372.33
River Rch & RM=13117,76,12541.59
  4006.6 6197.39 8206.17 9921.4814485.3715411.19
River Rch & RM=13117,76, 12078.3
 4024.65 6227.02 8246.91 9972.3414559.6115484.48
River Rch & RM=13117,76,   11615
 4029.44 6234.93 8257.82    998614579.5615504.29
River Rch & RM=13117,76,11151.71
 4095.36 6343.49 8407.42 10173.114852.7215774.61
River Rch & RM=13117,76,10688.42
 4098.47 6348.63  8414.510181.9614865.6715787.44
River Rch & RM=13117,76,10225.13
 4127.52 6396.87  8481.310265.8414988.1315909.52
River Rch & RM=13117,76,9918.265
 4157.59 6447.18 8551.2610354.04 15116.916038.88
River Rch & RM=13117,76,9156.912
 4166.32 6461.86 8571.7610379.9515154.7316077.09
River Rch & RM=13117,76,9016.081
 4168.43 6465.43 8576.7410386.2615163.9516086.43
River Rch & RM=13117,76,5945.667
 4214.95  6544.5 8687.7310527.2515369.7916296.37
River Rch & RM=13117,76,4166.777
 4253.77 6611.15  8781.810647.3115545.0716476.68
River Rch & RM=13117,76,2241.992
 4693.11 7378.27 9875.4912055.1817600.5618610.57
River Rch & RM=13117,76,946.0878
 4780.88 7532.2110095.6612339.4318015.5719039.83
River Rch & RM=13117,76,       0
 4803.75 7572.43 10153.312413.9518124.37 19152.5
Boundary for River Rch & Prof#=13117,76,1
Up Type= 0
Dn Type= 2
Boundary for River Rch & Prof#=13117,76,2
Up Type= 0
Dn Type= 2
Boundary for River Rch & Prof#=13117,76,2
Up Type= 0
Dn Type= 2
Boundary for River Rch & Prof#=13117,76,2
Up Type= 0
Dn Type= 2
Boundary for River Rch & Prof#=13117,76,2
Up Type= 0
Dn Type= 2
Boundary for River Rch & Prof#=13117,76,2
Up Type= 0
Dn Type= 2

--- 13117_ras.g01 (geometry) ---

Geom Title=13117
Program Version=4.10

River Reach=13117,76
Reach XY= 30
 904246.16424835809281.046380877904649.972467185809202.982181174
905640.653621498807963.020638357 906168.22115928808153.379669262
907299.016322944807817.046632974907876.292740881808145.771272558
 908231.04885608808001.766903381909165.944689425806582.496070051
909480.471427889806549.906062272 909793.11482832805407.582875576
911232.933606865804202.032076558910330.646197172803361.876661549
910888.600939396803072.513431157910689.382189423802329.023847825
911178.317120197802114.381622215910973.311149629801866.587952423
911200.710011068800968.168941398911889.147284421800493.985157367
911571.871372163799888.992266611912322.908539893799637.768019678
912384.074564933799079.786239071912901.461598993 798687.99089994
912951.194527657797464.655698444913936.228254289796499.133801532
914037.574196012796066.435225021913349.983827297794759.771200199
913471.137945206794110.867888285914759.144920917 792325.52269042
914972.686587575789981.772690457915752.200476472789368.925468199

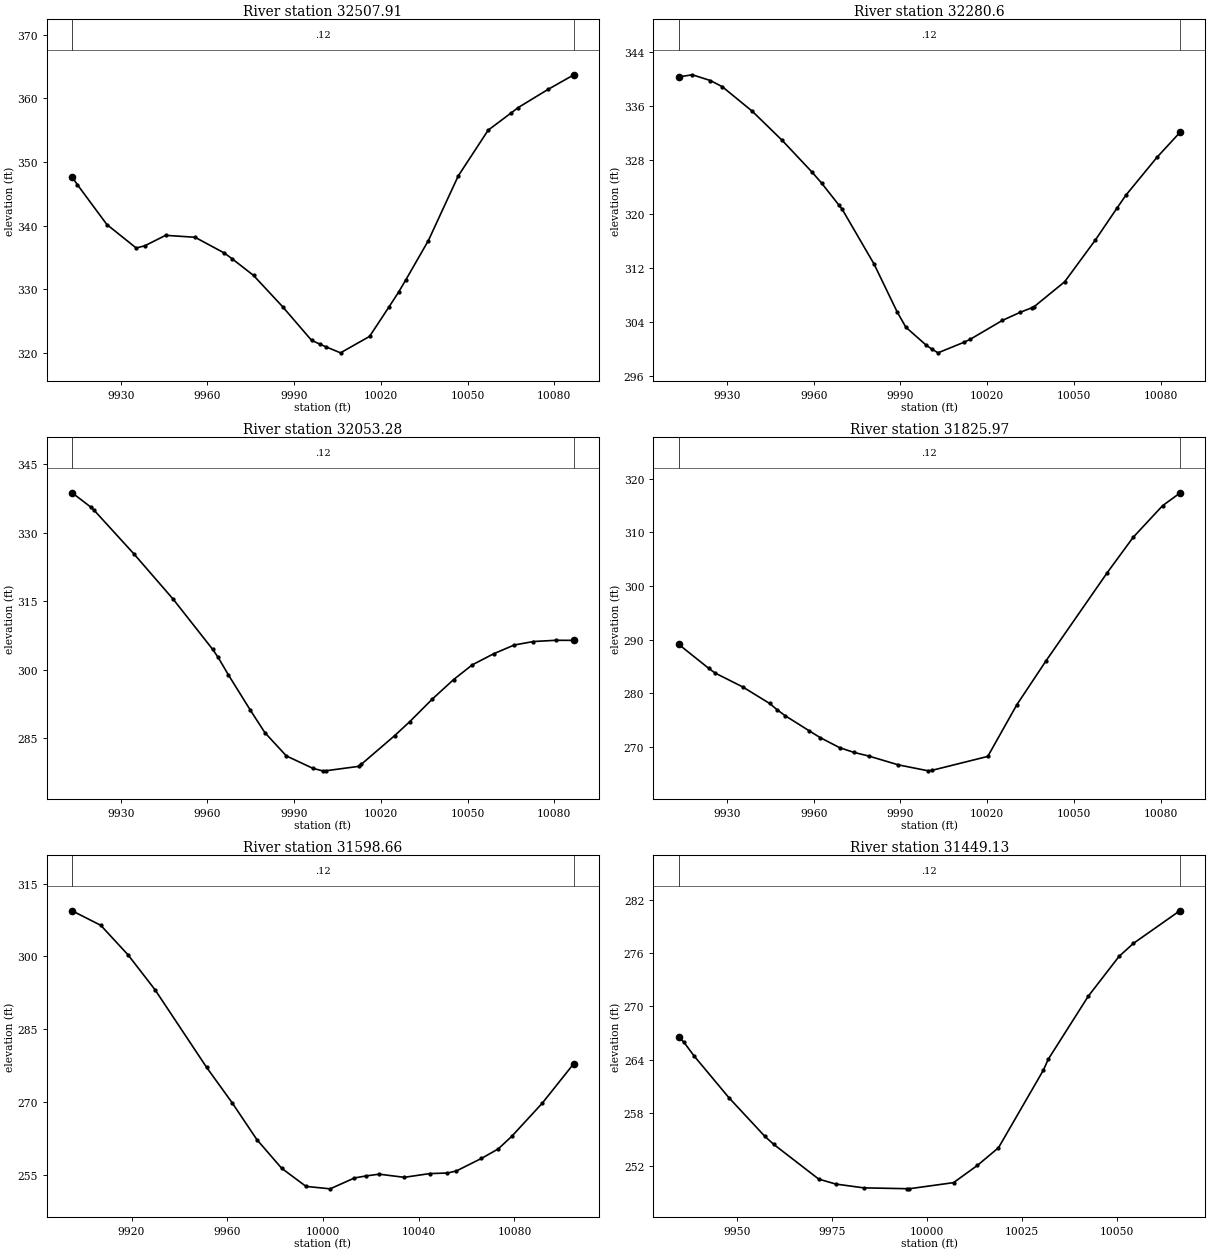
Type RM Length L Ch R = 1 ,32507.91,227.311400,227.311400,227.311400
XS GIS Cut Line= 6
904259.520056496809366.837312897904249.591638486809312.362633047
904247.182613088809282.027672505904247.145539978809280.028016138
904244.416405132809252.512149219904229.409889228809196.375727706
#Sta/Elev= 26
9913.197347.65339915.065346.4314 9925.23 340.1879935.395336.48849938.406336.8532
9945.559338.48789955.724338.18329965.889335.6978 9968.57334.79859975.955332.1874
9985.987 327.2849996.018321.9874    9999321.3624   10001320.960810006.05320.0131
 10016.1322.597710022.74327.175810026.15329.565610028.65331.496810036.43337.6575
10046.78347.835710057.13355.025810065.11357.740910067.48358.564210077.83361.4275
10086.76 363.728
#Mann= 3 , 0 , 0
9913.197    0.12       09913.197    0.12       010086.76    0.12       0
#XS Ineff= 2 , 0
       0                               0
Bank Sta=9913.197,10086.76
Exp/Cntr=0.3,0.1

Type RM Length L Ch R = 1 , 32280.6,227.311500,227.311500,227.311500
XS GIS Cut Line= 6
904487.863982727809309.607807446904473.471158068809256.172143566
904460.786490472809228.527295367904459.821079754 809226.77572974
904446.388041745809199.469673965904427.602476933809147.379672397
#Sta/Elev= 28
9913.244340.36029918.016340.67959924.256339.82679928.372338.91429938.729335.2827
9949.085 330.9669959.441 326.2469962.706324.64049968.584321.44329969.874320.7329
9980.876312.62999988.897305.51419991.878303.2717    9999300.5759   10001300.0011
10002.98299.475910011.92301.033110014.12301.478810025.27 304.28310031.43305.4807
10035.52  306.1710036.18306.293710046.81310.006710057.44316.2058   10065320.9847
10068.07322.8837 10078.7328.431710086.81332.2009
#Mann= 3 , 0 , 0
9913.244    0.12       09913.244    0.12       010086.81    0.12       0
#XS Ineff= 2 , 0
       0                               0
Bank Sta=9913.244,10086.81
Exp/Cntr=0.3,0.1

Type RM Length L Ch R = 1 ,32053.28,227.311500,227.311500,227.311500
XS GIS Cut Line= 6
904730.591952943809239.432790585904691.064149812809202.643110047
904665.670384433809183.502402196904664.064188376809182.310708348
904634.530094992809160.327937491904600.763634068809124.880493748
#Sta/Elev= 26
9913.201338.77179919.708335.6201 9920.84334.93129934.501 325.4399948.163315.4558
9961.824304.45319963.741302.6709  9967.2298.93039974.794291.19079979.898286.1826
9987.317281.08369996.512278.35959999.835277.8126   10001277.8315 10012.3278.7902
10013.24279.246610024.77285.519510029.99288.584710037.82293.554410045.18297.8234
10051.63301.044710058.99 303.46610066.13 305.396 10072.8306.161610080.63306.4362
10086.77306.4167
#Mann= 3 , 0 , 0
9913.201    0.12       09913.201    0.12       010086.77    0.12       0
#XS Ineff= 2 , 0
       0                               0
Bank Sta=9913.201,10086.77
Exp/Cntr=0.3,0.1

Type RM Length L Ch R = 1 ,31825.97,227.311400,227.311400,227.311400
XS GIS Cut Line= 6
904763.848906439808991.689171794904732.651668095808972.204501444
904710.251127236  808964.3335045 904652.44122817808974.220126777
904623.796853438 808973.02147675904598.963095325808968.419048019
#Sta/Elev= 22
 9913.27 289.1779923.703284.68489925.897283.81279935.493281.21139944.775278.1337
9947.283277.00549950.052275.88689958.457273.04129962.238271.77779968.998269.8937
9973.893269.02669979.145268.32489989.256266.69999999.625 265.585   10001265.6934
10020.18268.270310030.25277.910310040.28286.0455 10061.5302.513510070.45309.0943
10080.62314.983910086.76317.3936
#Mann= 3 , 0 , 0
 9913.27    0.12       0 9913.27    0.12       010086.76    0.12       0
#XS Ineff= 2 , 0
       0                               0
Bank Sta=9913.27,10086.76
Exp/Cntr=0.3,0.1

Type RM Length L Ch R = 1 ,31598.66,149.534500,149.534500,149.534500
XS GIS Cut Line= 6
904935.529382353808885.884695719904907.035717117808870.291514043
904878.201032133808858.677209972904797.846292195 808839.60517312
904775.615611107808828.785270465904743.165557591808807.820525385
#Sta/Elev= 22
9895.143309.38369907.146306.38559918.545300.29829929.819293.1112 9951.38277.1157
9962.027269.84139972.388262.22889982.749 256.331 9992.91252.600910003.01252.0972
10013.16 254.33810018.17254.770310023.48255.118510033.98254.470710044.65255.2415
10052.01255.352710055.78 255.78610066.21258.359110073.19260.302810078.85262.8894
10091.62269.728810104.85277.9149
#Mann= 3 , 0 , 0
9895.143    0.12       09895.143    0.12       010104.85    0.12       0
#XS Ineff= 2 , 0
       0                               0
Bank Sta=9895.143,10104.85
Exp/Cntr=0.3,0.1

Type RM Length L Ch R = 1 ,31449.13,77.777000,77.777000,77.777000
XS GIS Cut Line= 2
904916.190846682808737.201034829 904804.53506276808666.334633201
#Sta/Elev= 21
9934.567266.54829935.977265.95939938.674 264.4129947.821259.73289957.336255.3685
9959.665254.4717 9971.51250.57279975.997250.01489983.354249.58789994.658249.4928
9995.198249.476610007.04250.172910013.32252.107210018.89 254.09710030.73262.8268
10031.98264.029110042.57271.141510050.64 275.59510054.42277.060610066.26 280.609
10066.81280.7337
#Mann= 3 , 0 , 0
9934.567    0.12       09934.567    0.12       010066.81    0.12       0
#XS Ineff= 2 , 0
       0                               0
Bank Sta=9934.567,10066.81
Exp/Cntr=0.3,0.1

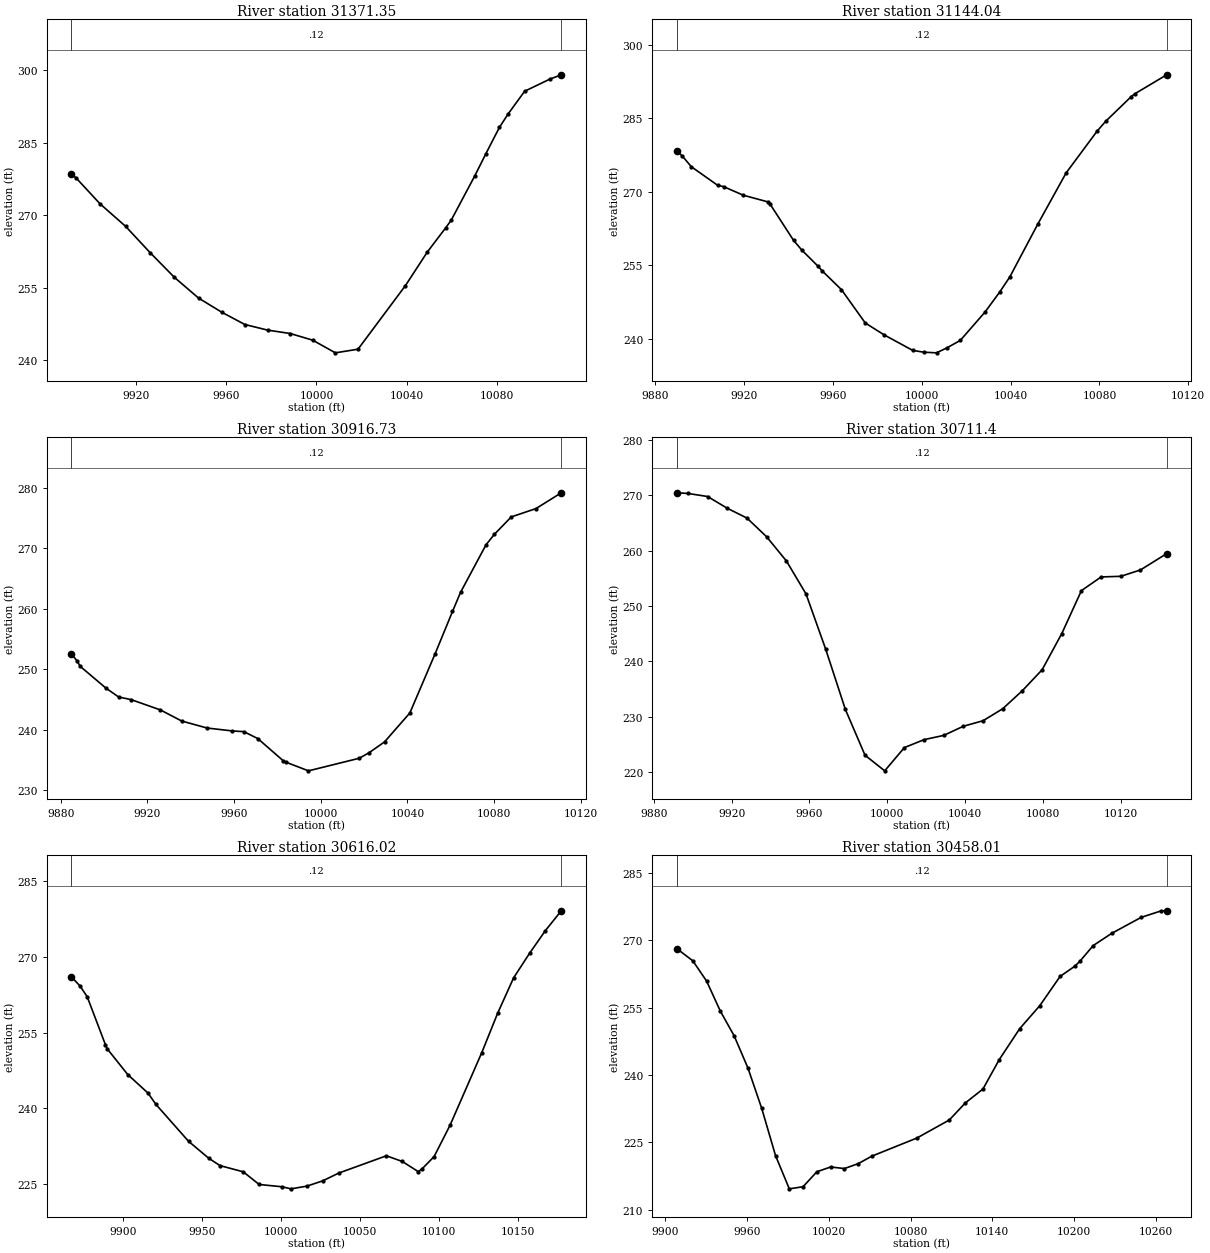
Type RM Length L Ch R = 1 ,31371.35,227.311400,227.311400,227.311400
XS GIS Cut Line= 6
 904946.01605602808756.119632189904921.590742988808702.876834945
904916.805331605808679.515044922904910.673963675808614.268073723
904899.382400503808580.355165144904884.395764408808550.437596333
#Sta/Elev= 25
9891.308278.56569893.448277.65949903.942272.35889915.303 267.6919926.293262.1862
 9937.01257.10129947.728252.81069958.044249.87819968.251247.3462 9978.37246.1834
9988.382 245.4829998.394244.096110008.41241.477310018.47242.229710039.49255.3878
10049.26 262.38110057.45267.4152 10059.8 268.92610070.34278.175510075.23282.7394
10081.22288.166710085.02290.912810092.41295.654210103.59298.166310108.69299.0682
#Mann= 3 , 0 , 0
9891.308    0.12       09891.308    0.12       010108.69    0.12       0
#XS Ineff= 2 , 0
       0                               0
Bank Sta=9891.308,10108.69
Exp/Cntr=0.3,0.1

Type RM Length L Ch R = 1 ,31144.04,227.311500,227.311500,227.311500
XS GIS Cut Line= 6
905180.517918061808656.220543589905131.654670312808628.319302811
905064.162547876808602.570564367905043.291860697808592.181771669
905018.977462487808572.639037879904994.616141885808544.015984372
#Sta/Elev= 30
9889.636  278.269891.929277.41289896.153275.14579907.965271.3667 9910.72271.0747
9919.608269.32199930.891267.93939931.523267.58019942.174260.13019945.948258.1139
9953.076254.9035 9955.22253.82799963.786250.04789974.495243.24879983.151240.7809
9995.915237.6427   10001237.2808 10006.6237.153710011.32238.179910017.29239.6863
10028.42245.466210035.17249.638710039.59 252.63810052.14263.368810064.97273.8811
10078.83282.350610082.73284.396210094.26289.438510095.86290.016910110.28293.9157
#Mann= 3 , 0 , 0
9889.636    0.12       09889.636    0.12       010110.28    0.12       0
#XS Ineff= 2 , 0
       0                               0
Bank Sta=9889.636,10110.28
Exp/Cntr=0.3,0.1

Type RM Length L Ch R = 1 ,30916.73,205.326300,205.326300,205.326300
XS GIS Cut Line= 2
 905286.30402675808538.502837373905168.924552926808345.256142662
#Sta/Elev= 27
9884.931 252.5659887.442251.41729889.029250.48119900.729246.93169906.705245.4348
9912.429 245.0069925.967243.3012 9935.83241.4622 9947.53240.3091 9959.23239.8263
9964.492239.7121 9970.93 238.566 9982.63234.91619983.755234.68879994.331233.2358
10017.73235.311810022.28 236.22210029.43238.015910041.13242.802110052.83252.6198
 10060.8259.561210064.53262.729510076.23270.549310080.07272.288710087.93275.1841
10099.33276.561610111.03279.1734
#Mann= 3 , 0 , 0
9884.931    0.12       09884.931    0.12       010111.03    0.12       0
#XS Ineff= 2 , 0
       0                               0
Bank Sta=9884.931,10111.03
Exp/Cntr=0.3,0.1

Type RM Length L Ch R = 1 , 30711.4,95.377900,95.377900,95.377900
XS GIS Cut Line= 2
905450.639880784808296.377937533905201.666523412808258.955561732
#Sta/Elev= 26
9891.874270.44819897.577270.32639907.689269.77229917.802267.64459927.914265.8759
9938.026262.49119948.139258.14459958.251252.17369968.363242.19189978.476231.3009
9988.588223.0216  9998.7220.204410008.81224.407210018.93225.837710029.04226.6109
10039.15228.263610049.26229.259710059.37231.426410069.49 234.703 10079.6238.4622
10089.71245.004210099.82252.773410109.94255.240210120.05255.355710130.16256.5047
10143.64 259.456
#Mann= 3 , 0 , 0
9891.874    0.12       09891.874    0.12       010143.64    0.12       0
#XS Ineff= 2 , 0
       0                               0
Bank Sta=9891.874,10143.64
Exp/Cntr=0.3,0.1

Type RM Length L Ch R = 1 ,30616.02,158.011900,158.011900,158.011900
XS GIS Cut Line= 3
905438.420329502808262.774171508905379.613738957808189.456863816
905165.007869566808165.017761251
#Sta/Elev= 30
9867.403266.0344 9872.87264.19689877.369262.08659888.852252.63549890.188251.7262
9903.008246.69649915.827243.02779920.817240.79739941.465233.49159954.285230.1205
9961.391228.67059976.099227.44469986.163224.936610000.78224.476410006.29224.0727
10016.36224.606110026.42225.657610036.49 227.18710066.68230.614910076.75229.4902
10086.81227.486410089.16 227.99310096.87 230.45210106.94236.636810127.07251.0483
10137.13258.8574 10147.2265.839210157.26 270.67810167.33275.199510177.38279.1089
#Mann= 3 , 0 , 0
9867.403    0.12       09867.403    0.12       010177.38    0.12       0
#XS Ineff= 2 , 0
       0                               0
Bank Sta=9867.403,10177.38
Exp/Cntr=0.3,0.1

Type RM Length L Ch R = 1 ,30458.01,229.262600,229.262600,229.262600
XS GIS Cut Line= 4
905464.386875976808266.592781283905439.947773412808110.029780482
905408.635173252808061.151575354905312.406206905807954.994223591
#Sta/Elev= 30
9908.396268.10819920.129265.3962 9930.25260.88289940.371254.17689950.492248.6921
9960.613241.52069970.734232.54159980.855222.05079990.977214.6409 10001.1215.1139
10011.22218.441610021.34219.505410031.46219.156210041.58 220.248 10051.7221.9293
 10084.7225.949910108.46229.959910120.33233.774910133.21236.8602 10145.2243.4124
 10160.2250.293110174.98255.419810189.87261.926710200.69264.197910204.76265.4238
10214.19268.794810227.68271.496210249.43275.071910264.32276.540210268.18276.5015
#Mann= 3 , 0 , 0
9908.396    0.12       09908.396    0.12       010268.18    0.12       0
#XS Ineff= 2 , 0
       0                               0
Bank Sta=9908.396,10268.18
Exp/Cntr=0.3,0.1

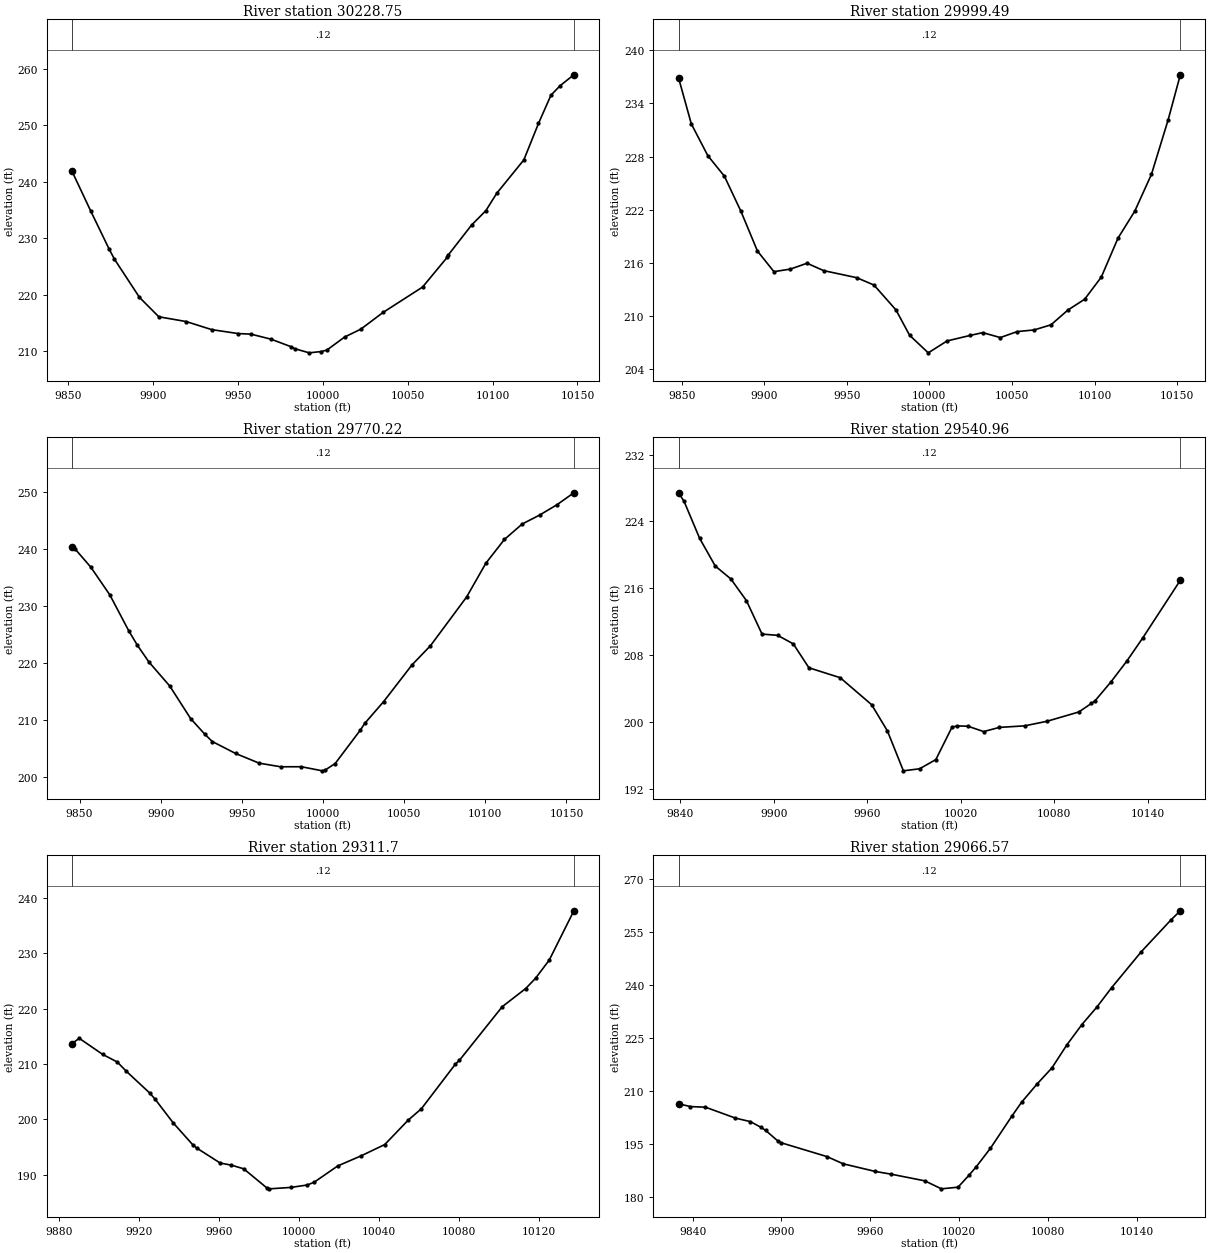
Type RM Length L Ch R = 1 ,30228.75,229.262500,229.262500,229.262500
XS GIS Cut Line= 6
905680.582860247808093.735881422905646.826299333808054.508021811
905611.368051039808025.006887564905543.821924396807993.946151197
905517.839652016807976.860504806905456.533839953807908.737733417
#Sta/Elev= 30
9852.118241.83579863.212234.75579873.895228.11539877.084226.29399891.846219.5236
9903.243216.08599919.296215.24659934.413 213.8119950.038 213.1129957.547213.0129
 9969.34 212.1239981.133 210.7929983.403210.43379991.867209.7003    9999209.9326
10002.28210.184610012.81 212.50910022.25  213.8810035.51216.871810058.73221.3542
10073.18226.600710073.84227.024910087.62232.3413   10096234.871810102.41237.9516
10118.39243.864510127.03250.321210134.36255.318310139.85257.028210147.88258.9429
#Mann= 3 , 0 , 0
9852.118    0.12       09852.118    0.12       010147.88    0.12       0
#XS Ineff= 2 , 0
       0                               0
Bank Sta=9852.118,10147.88
Exp/Cntr=0.3,0.1

Type RM Length L Ch R = 1 ,29999.49,229.262600,229.262600,229.262600
XS GIS Cut Line= 6
905793.519974059808082.744282676905795.577774174808018.627863057
905792.221398842807976.518813234 905785.71459748807953.687212077
905758.657099423807894.477673415905739.843454059807787.694418847
#Sta/Elev= 30
9848.097236.90269855.845231.6843 9865.85228.09019875.855 225.779 9885.86221.8165
9895.865217.31949905.871214.98179915.885215.27499925.917215.93269935.949215.1007
9956.068214.29759966.466213.46569979.773210.6532 9988.03207.78879999.323205.8035
10010.72207.149510024.66207.770910032.32208.087710042.94207.530110053.19208.2061
10063.42208.391710073.64208.970810083.87210.639310094.01211.860210104.12214.3685
10114.24218.776510124.35221.810710134.47225.975310144.58232.137110151.97237.2408
#Mann= 3 , 0 , 0
9848.097    0.12       09848.097    0.12       010151.97    0.12       0
#XS Ineff= 2 , 0
       0                               0
Bank Sta=9848.097,10151.97
Exp/Cntr=0.3,0.1

Type RM Length L Ch R = 1 ,29770.22,229.262500,229.262500,229.262500
XS GIS Cut Line= 6
905874.046492659808134.918147266905921.043566627808068.171071098
905997.265210211808001.354145629906022.736462537807973.768380996
906044.144213018 807940.22610086906061.995058972807895.139727598
#Sta/Elev= 30
9845.408240.3789 9847.26240.03439856.977236.82799868.641231.97539880.305225.6596
9885.634223.1087 9892.82220.14349905.645215.9184 9918.47210.20689927.228207.4562
9931.781206.18539946.136204.08499960.619202.3851 9973.86201.74379986.723201.7508
9999.584201.0292   10001201.1056 10007.5202.313410023.02208.192810025.71209.3677
10037.32213.184610054.82219.650110066.22223.028310088.49231.593610100.35 237.532
10111.76241.704610122.75 244.42510133.53246.005410144.12247.802810154.56249.9132
#Mann= 3 , 0 , 0
9845.408    0.12       09845.408    0.12       010154.56    0.12       0
#XS Ineff= 2 , 0
       0                               0
Bank Sta=9845.408,10154.56
Exp/Cntr=0.3,0.1

Type RM Length L Ch R = 1 ,29540.96,229.262600,229.262600,229.262600
XS GIS Cut Line= 6
906132.551043285808308.540131931906139.567614526808198.023333295
906155.542055935808129.787553333906157.422545974   808111.979265
906155.188162197808089.631242883906134.240269642807991.166396078
#Sta/Elev= 30
9838.935227.43269842.479226.40669852.489221.97459862.499218.66319872.509217.1152
9882.519 214.514 9892.53210.51289902.549210.36229912.585209.34159922.622206.4784
9942.695205.29019962.904202.05379973.045198.89979983.251194.13869993.638 194.385
10004.09195.486810014.48199.3775 10017.9199.518510024.71199.479510034.76198.8397
10044.82199.339210061.07199.525710075.31200.067910095.88201.186910103.89202.2058
10106.16 202.50610116.45204.780110126.73207.300210136.87210.0484   10161216.9562
#Mann= 3 , 0 , 0
9838.935    0.12       09838.935    0.12       0   10161    0.12       0
#XS Ineff= 2 , 0
       0                               0
Bank Sta=9838.935,10161
Exp/Cntr=0.3,0.1

Type RM Length L Ch R = 1 , 29311.7,245.126900,245.126900,245.126900
XS GIS Cut Line= 2
906356.860667375808098.056456497906224.916222931 807884.51478983
#Sta/Elev= 30
9886.665 213.6759890.258214.62139902.013211.70219909.229210.34979913.768208.6808
9925.523204.72589928.254203.59549937.278 199.3279947.278195.28029949.032194.7834
9960.787192.07099966.302191.70199972.542191.03239984.297187.51869985.327187.4136
9996.052187.668110004.35188.109410007.81188.619810019.56191.553910031.32193.3877
10043.07195.414110054.83199.840710061.42201.893810078.34 209.91710080.45210.6526
10101.85220.3329 10113.6  223.62 10118.5225.468310125.36228.756510137.68 237.671
#Mann= 3 , 0 , 0
9886.665    0.12       09886.665    0.12       010137.68    0.12       0
#XS Ineff= 2 , 0
       0                               0
Bank Sta=9886.665,10137.68
Exp/Cntr=0.3,0.1

Type RM Length L Ch R = 1 ,29066.57,245.126800,245.126800,245.126800
XS GIS Cut Line= 6
906473.292668275808212.983479041906481.904676749808158.254400501
906493.034481412 808118.01440697906537.176632304808024.185303847
906548.445239481807991.278890406906560.050406835807888.778685194
#Sta/Elev= 30
9830.471 206.3729838.553205.57329848.676205.40639868.922202.30459879.045201.3088
9885.874199.7571 9889.25198.84619897.485195.85259899.626195.33619930.873 191.379
9941.649189.35719963.201187.20039974.237186.39879996.824184.5215 10008.1182.2499
10019.31182.716210026.62186.059910031.43188.406310041.14193.713510055.58202.8024
10062.28206.8153 10072.6211.924610082.76216.544510092.92223.115210103.02228.8381
10113.15 233.81310123.17239.336310143.23249.534710163.28258.554610169.51261.0997
#Mann= 3 , 0 , 0
9830.471    0.12       09830.471    0.12       010169.51    0.12       0
#XS Ineff= 2 , 0
       0                               0
Bank Sta=9830.471,10169.51
Exp/Cntr=0.3,0.1

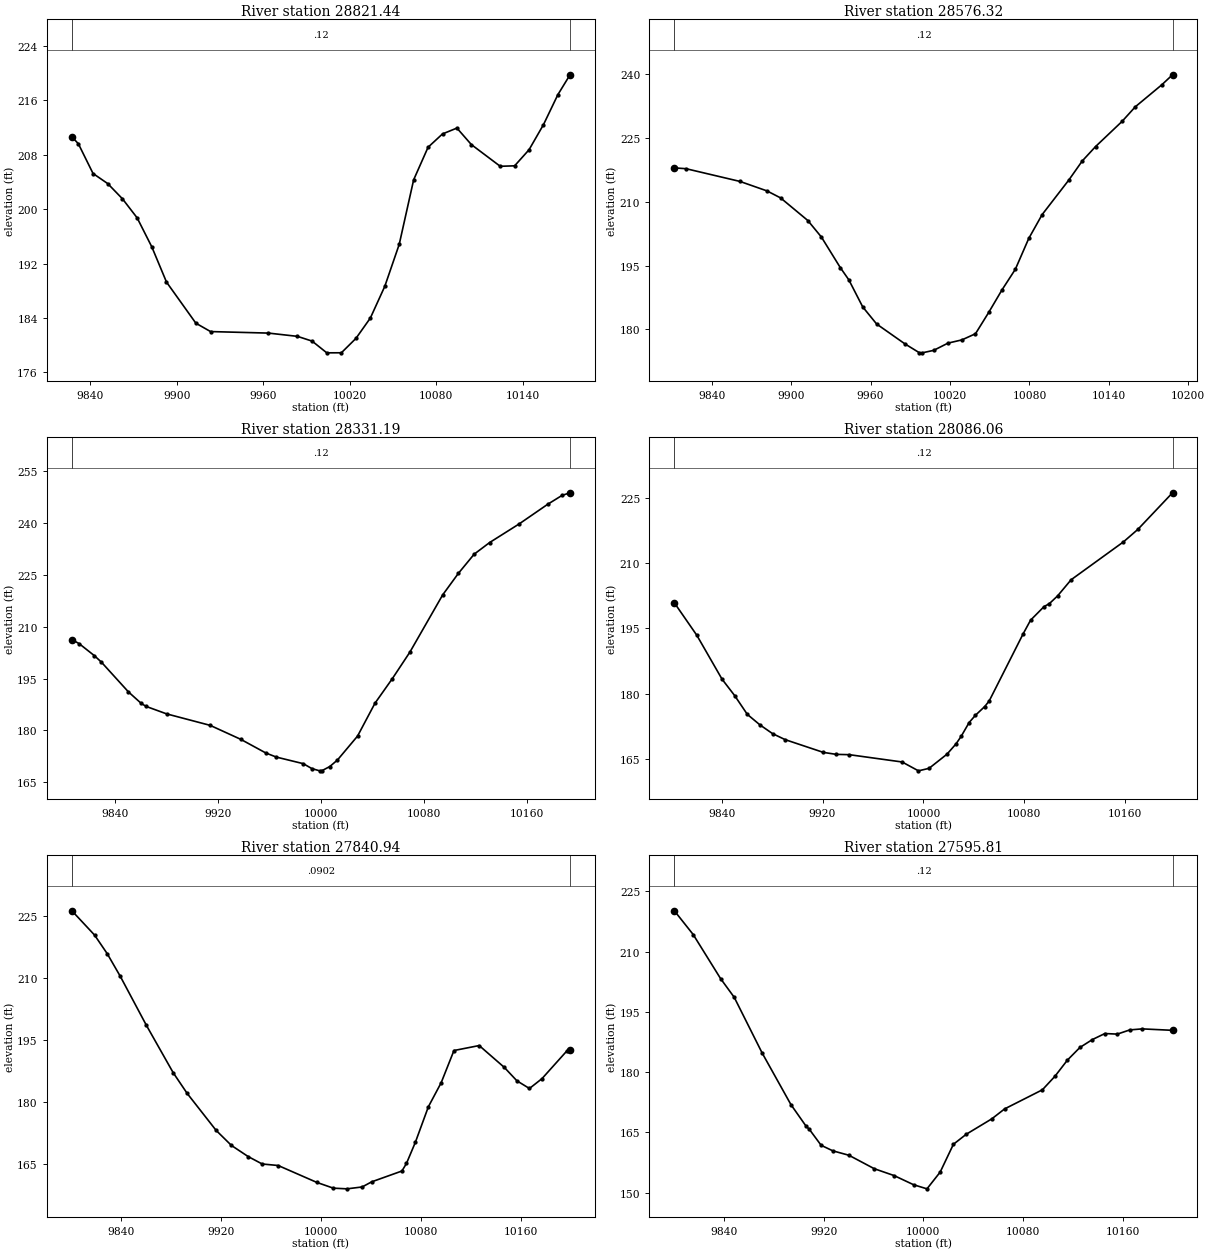
Type RM Length L Ch R = 1 ,28821.44,245.126900,245.126900,245.126900
XS GIS Cut Line= 6
906708.099595209808189.404874124906727.170582523808091.262927481
906731.439513673808035.287592283906737.987648932807998.011059103
906740.121782223807926.924064008 906737.83891462807846.581373552
#Sta/Elev= 30
 9827.27210.61849831.757209.59749841.944 205.2279852.131203.74259862.318201.5134
9872.505198.71659882.692194.44849892.879189.27469913.253183.2326 9923.44182.0036
9963.615181.77939983.678 181.3019993.857180.602110004.04178.878910014.16178.8883
10024.25180.999910034.26183.996710044.26188.649510054.27194.820310064.27204.2998
10074.27209.083910084.28211.041410094.28211.901410104.29 209.476 10124.3206.2878
 10134.3206.3555 10144.3208.718910154.31 212.40810164.31216.819710172.73219.7318
#Mann= 3 , 0 , 0
 9827.27    0.12       0 9827.27    0.12       010172.73    0.12       0
#XS Ineff= 2 , 0
       0                               0
Bank Sta=9827.27,10172.73
Exp/Cntr=0.3,0.1

Type RM Length L Ch R = 1 ,28576.32,245.126800,245.126800,245.126800
XS GIS Cut Line= 6
906945.983692995808313.693133872906919.868866712808191.170578197
906886.105768145808096.449347011906885.449539903808074.022218365
 906895.76134591807994.178447772 906893.88844867807946.923469841
#Sta/Elev= 30
9811.795217.91939820.648217.72449861.382214.73539881.766212.51289892.046210.8682
9912.604205.56489922.884201.67719937.099194.53039943.579191.6415 9954.08185.2819
 9964.58181.2725 9985.95176.6074  9996.8174.5375    9999174.501410007.66175.0816
 10018.5 176.78310028.98177.537510039.26178.983910049.27183.997610059.27189.2699
10069.38194.122710079.49201.348210089.61206.952310109.84 215.09510119.92219.5442
10129.95222.915610149.99228.8281   10160232.258710180.02237.4248 10188.1239.7718
#Mann= 3 , 0 , 0
9811.795    0.12       09811.795    0.12       0 10188.1    0.12       0
#XS Ineff= 2 , 0
       0                               0
Bank Sta=9811.795,10188.1
Exp/Cntr=0.3,0.1

Type RM Length L Ch R = 1 ,28331.19,245.126900,245.126900,245.126900
XS GIS Cut Line= 6
907187.332434451808119.696490741907141.840384071 808055.73985431
907050.845204419807966.558478209907005.575721588807916.885151392
906977.956474747807877.405717817906948.451362623807819.370667258
#Sta/Elev= 30
9806.702206.30269812.283205.14969824.168201.64679829.524199.80919850.614191.1445
9860.564187.81229864.326186.95149880.263 184.7859913.977181.46929937.763177.4149
9957.229 173.4589965.348172.27789986.269170.36739992.932168.9409    9999168.2913
   10001168.388710006.87169.548210012.74171.412110028.38178.362210041.91 187.886
10055.44195.037310068.97202.667210094.45219.265210106.65225.510610118.86231.0487
10130.89234.427410153.83239.825610175.98245.516810187.04248.071710193.27248.8356
#Mann= 3 , 0 , 0
9806.702    0.12       09806.702    0.12       010193.27    0.12       0
#XS Ineff= 2 , 0
       0                               0
Bank Sta=9806.702,10193.27
Exp/Cntr=0.3,0.1

Type RM Length L Ch R = 1 ,28086.06,245.126900,245.126900,245.126900
XS GIS Cut Line= 6
907293.752149812 808022.77456153907289.566144909807931.456140103
 907281.74987074807886.409830805907270.540663513807856.848655068
907222.414425661807760.489438861907182.740798273807648.927244307
#Sta/Elev= 30
9802.528200.84999820.321193.40129840.342183.30799850.353179.53429860.363175.2325
9870.374172.81169880.384170.80399890.395169.41899920.641166.49249930.898166.0373
9941.217165.96549983.122164.28769996.072162.253310004.48162.8275 10018.7166.0823
10025.83168.434610030.02170.216410036.23173.342510041.18174.998410048.64177.0322
10052.16 178.30810079.08193.727310084.96196.858810095.67199.987410099.76200.6336
10106.39202.4403 10117.1206.144710158.57214.839810170.05217.722710197.52226.1296
#Mann= 3 , 0 , 0
9802.528    0.12       09802.528    0.12       010197.52    0.12       0
#XS Ineff= 2 , 0
       0                               0
Bank Sta=9802.528,10197.52
Exp/Cntr=0.3,0.1

Type RM Length L Ch R = 1 ,27840.94,245.126800,245.126800,245.126800
XS GIS Cut Line= 6
907343.767635567808072.843002474 907361.85329127808001.472566345
907388.351230026807954.845310492907471.898077649807903.179238216
907492.048306934807879.187286591907512.760799326  807742.6066027
#Sta/Elev= 30
9800.884226.19219819.023220.33039829.188 215.8189839.507210.41829860.471198.5487
9881.866187.13699893.014182.15299916.142  173.249928.405169.59849941.778 166.916
9953.006165.12129965.795 164.7549996.597160.689510009.89159.2897 10020.8159.1263
 10032.9159.578210040.56160.818510064.71163.426110068.33165.239810075.44170.3323
10085.87178.929210096.09184.717510106.32 192.488 10126.5193.686810146.61188.4068
10156.64 185.18210166.66183.328210176.68185.703710196.72192.437910199.12192.6938
#Mann= 3 , 0 , 0
9800.884  0.0902       09800.884  0.0902       010199.12  0.0902       0
#XS Ineff= 2 , 0
       0                               0
Bank Sta=9800.884,10199.12
Exp/Cntr=0.3,0.1

Type RM Length L Ch R = 1 ,27595.81,245.126900,245.126900,245.126900
XS GIS Cut Line= 6
907595.434489663808038.788561804907620.760282288807982.482838744
907655.645953126807927.238788173907661.149012195807910.403314881
907627.695285002807785.450957616907624.156428069807660.752094514
#Sta/Elev= 30
9800.336220.13369815.455214.21719837.385203.2693 9848.35198.60289870.717184.7637
9893.813171.91539905.923 166.563 9908.64165.73839918.049161.78699927.461160.4041
9940.337159.3083 9960.69155.95919976.536154.25659992.274151.966210002.93150.9535
10013.52 155.11810024.12162.033710034.47164.541210054.95168.373610065.19170.8368
 10095.5175.594510105.54178.947110115.58182.987810125.61186.130510135.61188.0965
10145.61189.590310155.61  189.4510165.61190.495310175.61190.749810199.86190.3905
#Mann= 3 , 0 , 0
9800.336    0.12       09800.336    0.12       010199.86    0.12       0
#XS Ineff= 2 , 0
       0                               0
Bank Sta=9800.336,10199.86
Exp/Cntr=0.3,0.1

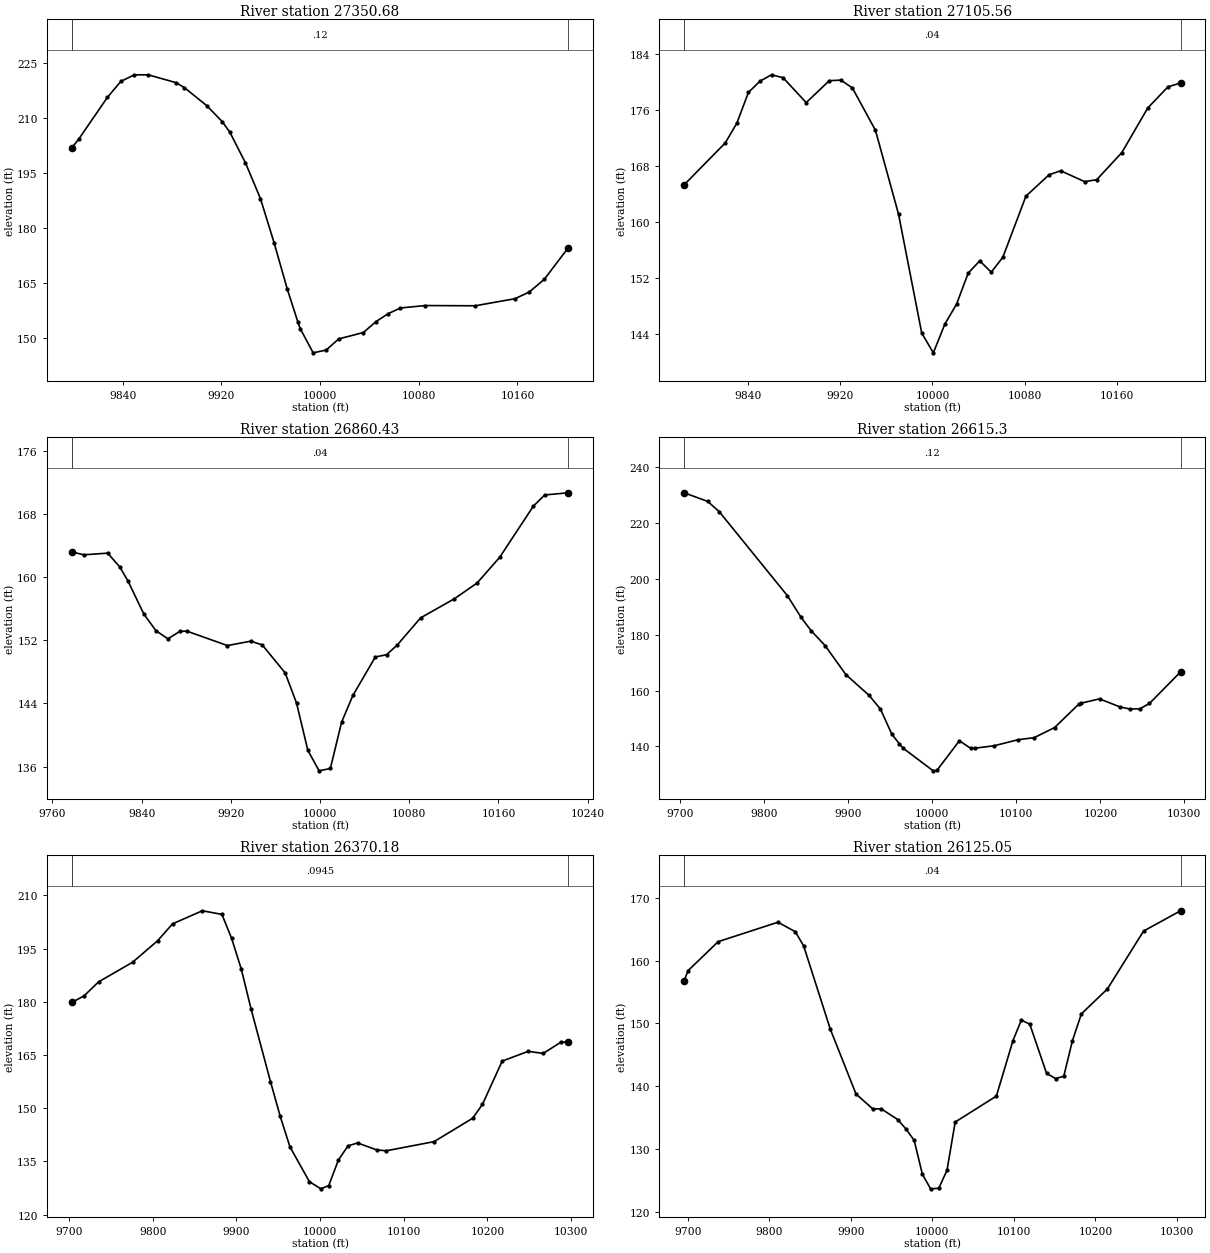
Type RM Length L Ch R = 1 ,27350.68,245.126900,245.126900,245.126900
XS GIS Cut Line= 6
907572.763704753808131.578331374907612.053323348808049.216153712
907651.747879048808007.581661896907706.878521557807987.283394538
907824.911876186807984.776513075907889.883582693807947.777107186
#Sta/Elev= 30
 9798.81   201.99804.504204.3195 9827.71215.69979838.583220.04599849.578221.8434
9860.916221.81799883.592219.6653 9890.15218.30629908.142213.43789920.799209.0343
9926.901206.17829939.566197.80199951.697188.07079962.721176.0603 9973.44163.3793
9982.113 154.2979983.935152.5818 9994.43 145.96110005.04146.729810015.13149.7637
10035.16151.509910045.18154.442110055.19 156.65110065.21158.202310085.24158.8673
10125.75158.800710158.02160.736810169.59162.5576 10181.8166.035710201.21174.6513
#Mann= 3 , 0 , 0
 9798.81    0.12       0 9798.81    0.12       010201.21    0.12       0
#XS Ineff= 2 , 0
       0                               0
Bank Sta=9798.81,10201.21
Exp/Cntr=0.3,0.1

Type RM Length L Ch R = 1 ,27105.56,245.126800,245.126800,245.126800
XS GIS Cut Line= 6
907881.214746551808360.619108916907873.309114944808213.499148509
907879.584802992 808122.12826811907877.319263267808049.572919004
907887.189650532808006.454003791907920.206611965807939.951457768
#Sta/Elev= 30
9784.788165.28579820.493171.28899830.518174.11339840.542178.49829850.566180.1104
 9860.59181.02029870.606180.59539890.617 177.0439910.629180.17549920.635180.2574
9930.641179.13639950.645173.08369970.648161.09499990.743144.109510000.81 141.275
10010.88145.413610020.95148.230510030.99152.6544   10041154.422910051.02152.8031
10061.04154.927610081.06163.665310101.13 166.72910111.25 167.29910131.92165.7453
10142.41166.018310164.19 169.89410186.67176.269610204.19179.299210215.14179.8468
#Mann= 3 , 0 , 0
9784.788    0.04       09784.788    0.04       010215.14    0.04       0
#XS Ineff= 2 , 0
       0                               0
Bank Sta=9784.788,10215.14
Exp/Cntr=0.3,0.1

Type RM Length L Ch R = 1 ,26860.43,245.126900,245.126900,245.126900
XS GIS Cut Line= 6
 908164.00297146808274.770699561908122.689802819808173.536649932
908102.188577772 808107.88451201908096.406375302 808077.95047215
908087.397653377808009.694731939908061.647626479807844.067678969
#Sta/Elev= 30
 9777.45163.25259788.003162.87399809.604163.08849820.405161.34379827.743159.5674
9842.006155.36489852.807153.25419863.607152.20669874.408 153.1669880.675153.1831
9916.948151.35379937.849151.9111 9948.22151.43489968.722 147.8889978.907144.0711
 9989.07138.05589999.178135.450810009.26135.748410019.35141.632710029.43145.0148
10049.59149.9088 10059.7150.191310069.45151.460310090.12 154.86210120.53157.3012
10140.81159.293110161.06162.557110191.35169.068910201.44170.471910222.57 170.749
#Mann= 3 , 0 , 0
 9777.45    0.04       0 9777.45    0.04       010222.57    0.04       0
#XS Ineff= 2 , 0
       0                               0
Bank Sta=9777.45,10222.57
Exp/Cntr=0.3,0.1

Type RM Length L Ch R = 1 , 26615.3,245.126800,245.126800,245.126800
XS GIS Cut Line= 6
908509.890184594808145.462296054908399.028842358808030.608764541
908254.074740216807898.272946256908206.276866098807850.138167389
908157.775383888807789.561550426908111.768405753807712.551673433
#Sta/Elev= 30
9704.394230.7772 9732.48227.68139746.206224.02259827.279193.98989843.707186.1841
9855.589181.44029872.222176.12079897.047165.7039 9924.52158.33219938.224153.3624
9951.633 144.4539960.403141.06059965.042139.4222   10001131.286710005.49131.4819
10032.16142.043810045.62 139.34910050.29139.387210073.21 140.239 10101.6142.3933
10121.32143.162910145.59146.789110174.07155.0737   10177155.475710199.02157.0499
10223.16 154.17410235.08153.4157   10247 153.471 10258.5155.385610295.57166.6998
#Mann= 3 , 0 , 0
9704.394    0.12       09704.394    0.12       010295.57    0.12       0
#XS Ineff= 2 , 0
       0                               0
Bank Sta=9704.394,10295.57
Exp/Cntr=0.3,0.1

Type RM Length L Ch R = 1 ,26370.18,245.126900,245.126900,245.126900
XS GIS Cut Line= 6
908684.177408077807893.547739172908620.474516278807848.107367876
908546.523221352807800.801497439908254.868899927807633.001480483
908219.116142099807609.090418004908181.350530969807579.680938205
#Sta/Elev= 30
9703.284 179.8189718.003181.68859735.223185.61639775.974191.15749805.857197.2165
9823.645201.97089859.258205.66899882.704204.65369894.318197.89029905.933189.1589
9917.547177.98729940.776157.49199952.391147.70759964.005139.11299987.234129.2947
   10001127.2577 10010.4128.180710021.95135.393510033.45139.372910044.87140.2011
10067.72138.232310079.15137.991810136.27140.566710182.44147.166510194.06151.0435
10217.71163.277310248.84166.033610266.74165.438310288.05 168.64110296.71168.6471
#Mann= 3 , 0 , 0
9703.284  0.0945       09703.284  0.0945       010296.71  0.0945       0
#XS Ineff= 2 , 0
       0                               0
Bank Sta=9703.284,10296.71
Exp/Cntr=0.3,0.1

Type RM Length L Ch R = 1 ,26125.05,549.552200,549.552200,549.552200
XS GIS Cut Line= 6
908778.828477809807618.759441048908696.577261495 807562.26989097
908627.785773682807528.996756641908562.611097237807510.405919728
908364.262719906807478.259792774908215.608019199807411.210295064
#Sta/Elev= 30
9695.523156.77589700.253158.40219737.318 163.0329810.618166.12419831.956164.6073
9842.125162.36089874.775149.11999906.343138.77679926.924136.40159937.214 136.412
9957.506134.70819967.633133.19649977.716131.39059987.774125.99899997.831123.6697
10007.89 123.76410017.96126.628810028.03 134.31110078.52138.4335 10098.9147.2814
10109.13 150.53310119.46149.897710140.12142.054110151.19141.234810161.19141.5913
10171.73 147.221 10182.8151.534210214.63 155.48810259.09164.718910304.48167.9473
#Mann= 3 , 0 , 0
9695.523    0.04       09695.523    0.04       010304.48    0.04       0
#XS Ineff= 2 , 0
       0                               0
Bank Sta=9695.523,10304.48
Exp/Cntr=0.3,0.1