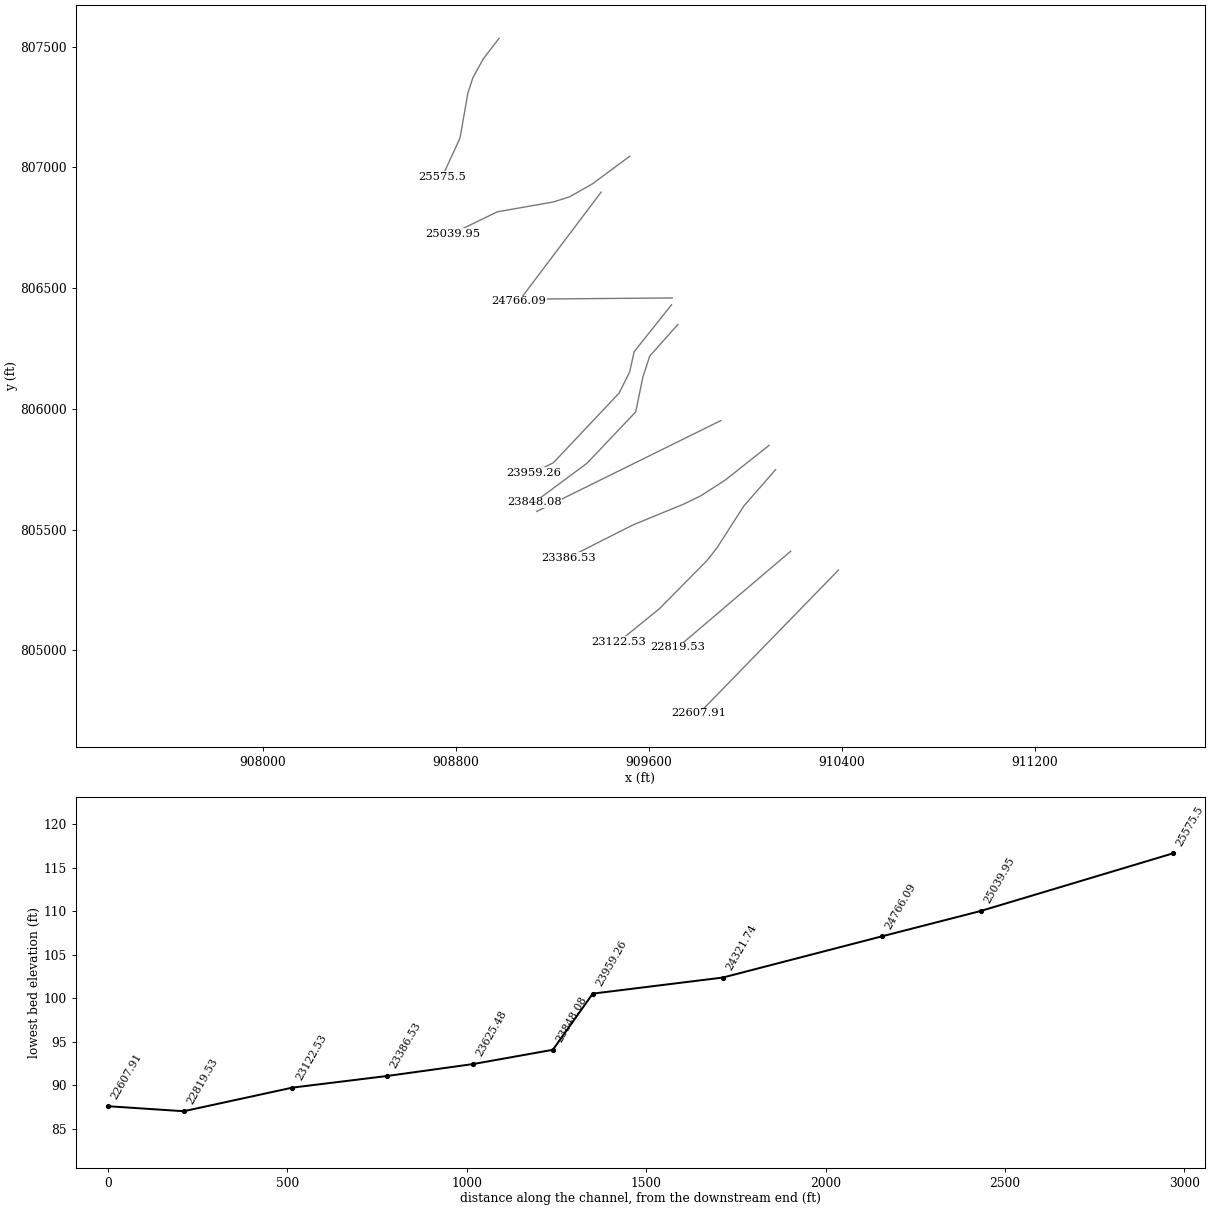
HEC-RAS study 13117_ras.prj: 13117

--- 13117_ras.g01 (geometry) --- (continued)

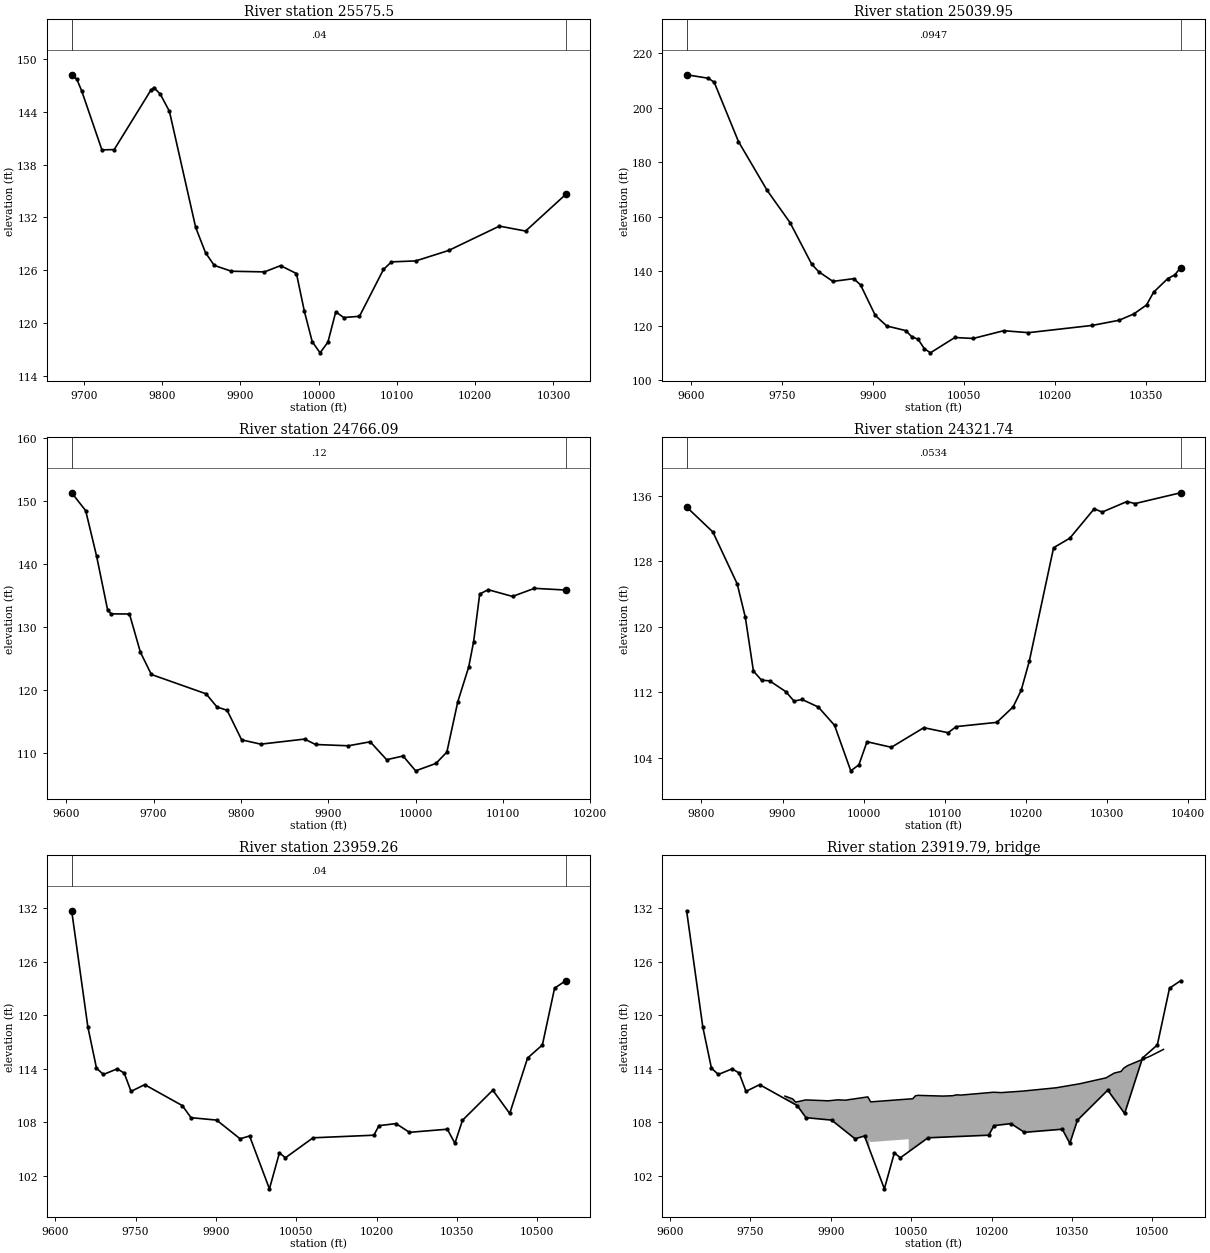
Type RM Length L Ch R = 1 , 25575.5,535.552200,535.552200,535.552200
XS GIS Cut Line= 6
908979.213869954807535.028927545908913.999533727807450.458065112
908870.279092814 807371.33438663908849.696776759807307.279388686
908817.255984399807122.134240485908743.001467689806960.671861594
#Sta/Elev= 30
9684.317148.19769691.011147.67019697.224 146.3399722.963139.6689 9738.67139.7031
9785.576 146.4559789.438146.74139797.542146.00059809.239 144.0479842.813  130.86
9855.362127.99159866.473126.55549888.409125.88859930.685125.81329951.325126.5263
9971.607125.62399981.738121.32869991.771117.8847 10001.8 116.62210011.82117.8382
10021.84121.274510031.94120.633510052.15120.771110082.82126.093710093.04126.9511
10124.11127.061610166.06128.244310230.96 131.01210264.48 130.45110315.71134.6111
#Mann= 3 , 0 , 0
9684.317    0.04       09684.317    0.04       010315.71    0.04       0
#XS Ineff= 2 , 0
       0                               0
Bank Sta=9684.317,10315.71
Exp/Cntr=0.3,0.1

Type RM Length L Ch R = 1 ,25039.95,273.853500,273.853500,273.853500
XS GIS Cut Line= 6
909521.260501829807046.778446177909366.647437126  806932.3805968
909271.339861789806878.245570842909203.559463621806856.948651205
908971.919054071806816.275664649908786.803102529806726.402172984
#Sta/Elev= 30
9592.447212.12849628.437210.85179637.992209.37869678.015187.59529725.401169.6382
9763.076157.85199798.761142.61039810.305139.82119833.868136.25529868.101137.2517
9879.378134.98269903.753123.75799922.672 119.8819953.846118.19019964.184115.8875
9974.361115.00249984.512 111.5999994.662110.014510035.01115.649110065.24115.2934
10115.62118.139610156.51117.424410261.86120.088910306.18121.988610330.36 124.308
10351.25127.581810362.97132.281910386.24137.277710397.95 138.65710407.56141.3165
#Mann= 3 , 0 , 0
9592.447  0.0947       09592.447  0.0947       010407.56  0.0947       0
#XS Ineff= 2 , 0
       0                               0
Bank Sta=9592.447,10407.56
Exp/Cntr=0.3,0.1

Type RM Length L Ch R = 1 ,24766.09,444.349700,444.349700,444.349700
XS GIS Cut Line= 2
909402.220908205806897.806316879 909061.50910265806446.417427991
#Sta/Elev= 30
9606.299151.29659622.344148.45289634.873141.20199647.401132.70999651.482132.0633
9672.459132.03739684.988125.96449697.517122.43079760.162119.3568 9772.69117.2582
9784.273116.73899800.871112.04139822.806111.36029872.922 112.1669885.451111.3075
9923.037111.10269948.095111.73649966.859108.89269985.682109.476510000.06107.1219
10023.27108.2969 10035.8   110.110048.33118.107810060.86123.651110066.45127.6598
10073.38135.199910083.05135.899410110.97134.829310136.03136.115110171.84135.8458
#Mann= 3 , 0 , 0
9606.299    0.12       09606.299    0.12       010171.84    0.12       0
#XS Ineff= 2 , 0
       0                               0
Bank Sta=9606.299,10171.84
Exp/Cntr=0.3,0.1

Type RM Length L Ch R = 1 ,24321.74,362.480100,362.480100,362.480100
XS GIS Cut Line= 3
909697.359797094806459.438261324909176.526463761806455.097983546
909089.720908205806439.907011324
#Sta/Elev= 30
9781.654 134.6089814.015131.55899844.016125.21569854.017121.14339864.017114.5706
9874.017113.45429884.018113.37569904.018112.04969914.019110.89969924.019111.0986
 9944.02110.17469964.021107.94239984.021102.38259994.022103.119710004.02105.9385
10034.02105.258110074.02107.652310104.03107.038510114.03107.786610164.03108.3042
10184.03110.178410194.03112.198310204.03115.757310234.03129.638210254.03 130.797
10284.03134.383610294.03133.993110324.36135.272510334.51135.030310390.63136.3469
#Mann= 3 , 0 , 0
9781.654  0.0534       09781.654  0.0534       010390.63  0.0534       0
#XS Ineff= 2 , 0
       0                               0
Bank Sta=9781.654,10390.63
Exp/Cntr=0.3,0.1

Type RM Length L Ch R = 1 ,23959.26,111.183200,111.183200,111.183200
XS GIS Cut Line= 6
909694.078505361806430.876938207909539.369942248806236.929489937
909520.769961691 806153.22957743 909476.55859851806064.806851067
909204.216601315805776.548763127909121.099238534   805735.874309
#Sta/Elev= 30
9630.801131.6892 9660.97118.68589677.114114.05419690.023113.3525 9715.84113.9806
9728.749113.51429741.658111.45729767.071112.20999837.321109.86189853.547108.5105
9901.372108.23819945.149106.14459962.835106.45899999.912100.537810018.57104.5688
10029.75104.0167 10081.3106.255910194.81106.547210204.42107.617910236.27107.8452
10261.25106.868410331.97107.217310346.11105.639510360.25108.217310416.82111.5902
 10448.4108.979510481.75115.192910509.38 116.65710532.13123.015410552.89123.8559
#Mann= 3 , 0 , 0
9630.801    0.04       09630.801    0.04       010552.89    0.04       0
#XS Ineff= 2 , 0
       09952.602        10058.85       0
Bank Sta=9630.801,10552.89
Exp/Cntr=0.3,0.1

Type RM Length L Ch R = 3 ,23919.79,,,
BEGIN DESCRIPTION:
END DESCRIPTION:
Bridge Culvert--1,0,-1,-1, 0
Deck Dist Width WeirC Skew NumUp NumDn MinLoCord MaxHiCord MaxSubmerge Is_Ogee
46.241600,18.700000,2.6,0, 32, 28, , , 0.95, 0, 0,0,,
 9814.38 9828.90 9834.32 9853.08 9895.32 9913.06 9926.91 9969.02 9972.13 9972.13
 9974.3310045.2910045.2910052.8710057.8710062.3610109.4910127.1610135.7110142.63
10203.4710218.1110256.7210320.6010364.5210413.5410429.1210441.6610446.6810454.21
10496.3910520.99
  110.93  110.61  110.25  110.50  110.40  110.51  110.47  110.84  110.52  110.52
  110.28  110.60  110.60  110.63  110.96  111.01  110.93  110.97  111.07  111.04
  111.36  111.32  111.48  111.86  112.31  112.97  113.51  113.69  114.06  114.35
  115.41  116.16
 -889.07 -889.39 -889.75 -889.50 -889.60 -889.49 -889.53 -889.16 -889.48  106.02
  105.78  106.10 -889.40 -889.37 -889.04 -888.99 -889.07 -889.03 -888.93 -888.96
 -888.64 -888.68 -888.52 -888.14 -887.69 -887.03 -886.49 -886.31 -885.94 -885.65
 -884.59 -883.84
 9814.38 9828.90 9834.32 9853.08 9895.32 9913.06 9926.91 9954.91 9954.91 9969.02
 9974.3310028.0710028.0710052.8710057.8710062.3610109.4910203.4710218.1110284.10
10349.8810413.5410429.1210441.6610446.6810454.2110496.3910520.99
  110.93  110.61  110.25  110.50  110.40  110.51  110.47  110.70  110.70  110.84
  110.28  110.52  110.52  110.63  110.96  111.01  110.93  111.36  111.32  111.62
  112.14  112.97  113.51  113.69  114.06  114.35  115.41  116.16
 -889.07 -889.39 -889.75 -889.50 -889.60 -889.49 -889.53 -889.30  106.20  106.34
  105.78  106.02 -889.48 -889.37 -889.04 -888.99 -889.07 -888.64 -888.68 -888.38
 -887.86 -887.03 -886.49 -886.31 -885.94 -885.65 -884.59 -883.84
BR Coef=-1 , 0 , 0 ,, 0 ,,,0.8,0,1,0,
WSPro=,,,, 1 ,,,, 0 ,,,, 0 ,,,,-1 ,-1 ,-1 , 0 , 0 , 0 , 0 , 0
BC Design=,, 0 ,, 0 ,,,,,,

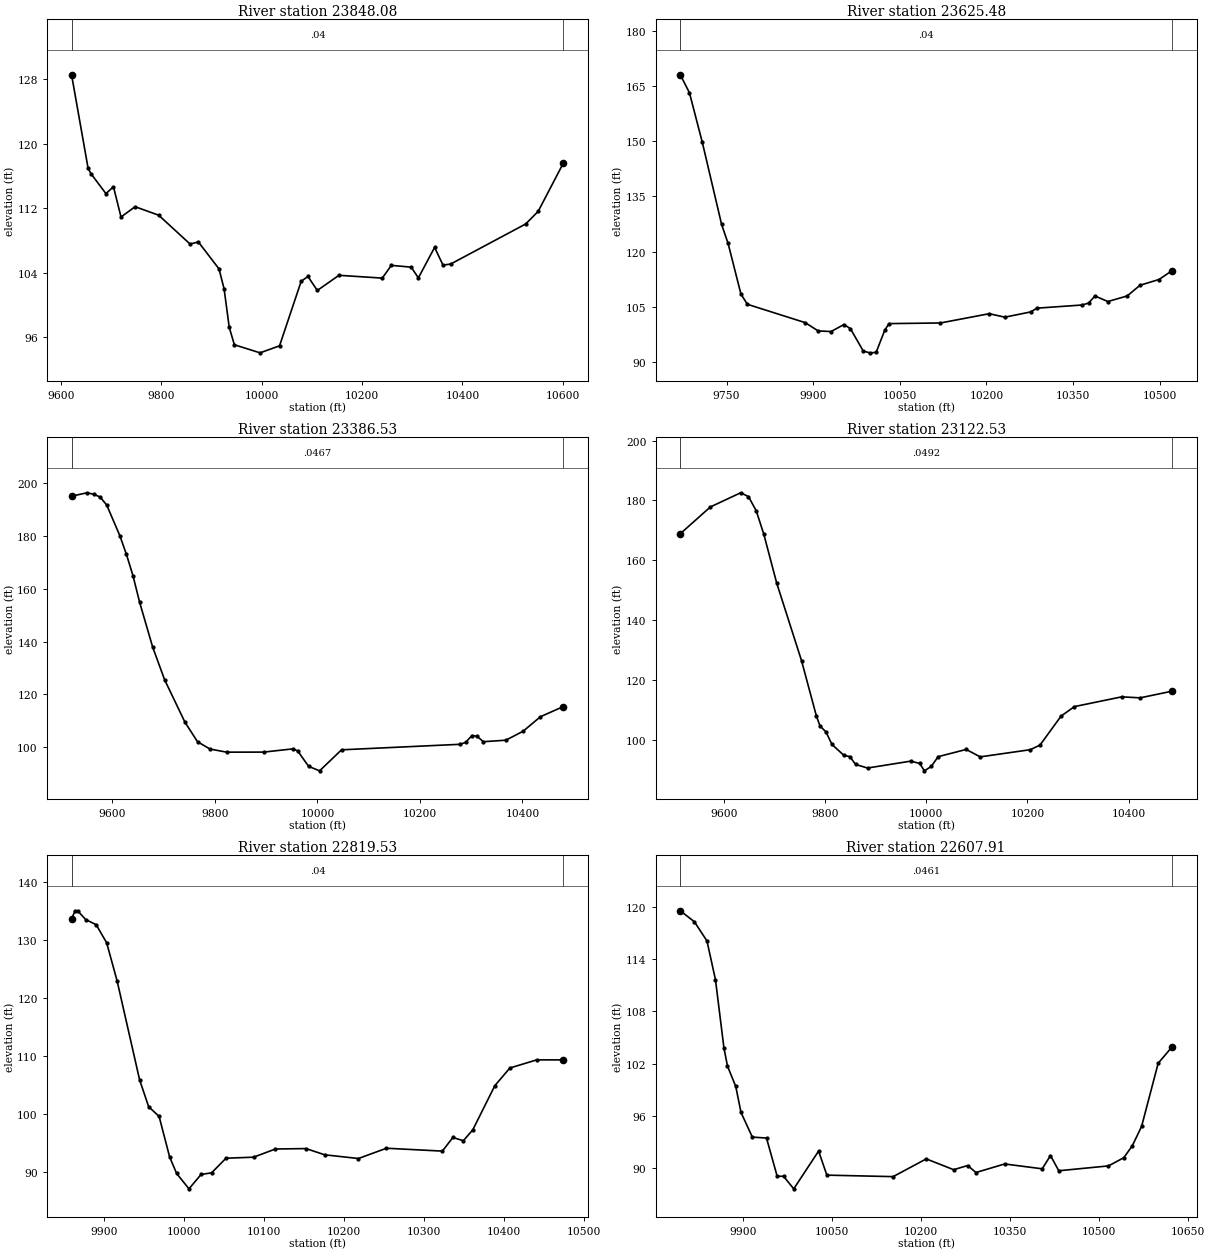
Type RM Length L Ch R = 1 ,23848.08,222.596400,222.596400,222.596400
XS GIS Cut Line= 6
 909720.60532327806349.528029954909603.887324472806218.662394938
909575.592052036806132.008123103909545.528325073805986.994851869
909343.924508967805774.780308599909124.636147589805612.082492093
#Sta/Elev= 30
9620.781128.51659653.647116.9702 9659.25 116.2929689.297113.80559704.321 114.658
9719.345110.90719747.444112.18559794.463111.13239856.983107.56439873.625107.8202
9914.759104.48299924.929102.00129935.09997.259189945.32995.095599996.50694.09491
 10035.494.9618110078.52102.948710091.99103.551210110.73101.818510153.91 103.693
10240.25103.346310258.31104.923610297.82104.703210312.21103.375810344.56107.1465
10361.34 104.95710376.61105.087710526.04110.043910550.94111.5961 10601.2117.5793
#Mann= 3 , 0 , 0
9620.781    0.04       09620.781    0.04       0 10601.2    0.04       0
#XS Ineff= 2 , 0
       0                10076.72       0
Bank Sta=9620.781,10601.2
Exp/Cntr=0.3,0.1

Type RM Length L Ch R = 1 ,23625.48,238.947600,238.947600,238.947600
XS GIS Cut Line= 2
909899.219230521805951.625761324909135.246874752805574.944947021
#Sta/Elev= 30
9669.747168.04329685.601163.1647  9707.9149.68599741.348127.34699752.569122.1976
9774.797108.44899785.946105.65039886.291100.6566 9908.5998.411199930.88998.24719
9953.188100.14229964.33799.046529986.63692.962099997.78692.4559910008.9492.55819
10023.9298.6117310031.23100.401510120.43100.575210204.83103.093710231.92102.1511
10276.52103.570810287.67104.602910365.72105.459210376.87105.972410388.02107.9121
10410.32106.405710443.76107.913410466.06110.8251 10498.8112.386410521.53114.7795
#Mann= 3 , 0 , 0
9669.747    0.04       09669.747    0.04       010521.53    0.04       0
#XS Ineff= 2 , 0
       0                               0
Bank Sta=9669.747,10521.53
Exp/Cntr=0.3,0.1

Type RM Length L Ch R = 1 ,23386.53,264.000000,264.000000,264.000000
XS GIS Cut Line= 6
910098.329312302805848.320472346909917.246983577 805705.08754278
909815.856508481  805639.8118011909745.593204698805605.666200282
909531.894952545805517.893411963909265.467515119805382.974757805
#Sta/Elev= 30
9520.304195.01689550.281196.3157 9563.13195.79219575.979194.71449588.828 191.696
9614.527180.05449627.376172.98129640.225 164.8649653.075154.88389678.584137.8906
9701.868125.53829741.457109.5209 9766.08102.0935 9790.3799.337779822.79798.16213
9895.04398.18302 9951.8299.400659961.33598.652589982.78192.7891910004.1991.09206
10047.0299.0487710277.78101.129210288.91101.832210301.57104.450510311.17104.1892
10323.74 102.11610367.53102.685710401.35106.091610435.17111.585410479.74115.4176
#Mann= 3 , 0 , 0
9520.304  0.0467       09520.304  0.0467       010479.74  0.0467       0
#XS Ineff= 2 , 0
       0                               0
Bank Sta=9520.304,10479.74
Exp/Cntr=0.3,0.1

Type RM Length L Ch R = 1 ,23122.53,303.002900,303.002900,303.002900
XS GIS Cut Line= 6
910125.658114435  805748.1808074909994.067553512805597.381612275
909882.864693804805424.330713532909841.342329238805371.524422251
909644.463158844805172.310191593909474.775049596805034.617421126
#Sta/Elev= 30
9513.994168.8871 9573.54177.83299633.388182.55379648.795181.28659664.203 176.512
9679.142168.70369704.573152.41519753.639126.53789782.916108.14469790.121104.7412
9802.063102.71649813.78298.56565 9837.2294.94444 9848.9494.513249860.65991.88358
9884.098 90.69649969.58592.999159987.26192.233589996.56289.7574510009.9791.21265
 10023.894.4930810079.1296.8952110106.7894.4196210205.8196.8133510225.0698.35508
10266.67108.020510292.99111.190610386.53114.452310422.95114.118710486.02116.3423
#Mann= 3 , 0 , 0
9513.994  0.0492       09513.994  0.0492       010486.02  0.0492       0
#XS Ineff= 2 , 0
       0                               0
Bank Sta=9513.994,10486.02
Exp/Cntr=0.3,0.1

Type RM Length L Ch R = 1 ,22819.53,211.624400,211.624400,211.624400
XS GIS Cut Line= 2
910188.457889598805410.122428719909719.707889598805011.684928719
#Sta/Elev= 30
9858.943133.64629863.481134.99429866.852134.94169876.606133.4825 9889.73132.5945
9902.855129.46919915.979122.86819944.055105.84729955.352101.21469968.47799.52894
9981.60192.551919990.37689.7004110005.8287.0477410020.9789.52837 10034.189.80449
10052.14 92.3298 10086.6 92.5048 10113.993.9156410152.2293.9902110175.6692.91537
10217.8492.2785110252.8694.0487510322.84 93.553210335.9695.9065610349.08 95.3395
10360.9597.2394510388.46104.837910407.27107.882710440.96109.291310474.15109.2823
#Mann= 3 , 0 , 0
9858.943    0.04       09858.943    0.04       010474.15    0.04       0
#XS Ineff= 2 , 0
       0                               0
Bank Sta=9858.943,10474.15
Exp/Cntr=0.3,0.1

Type RM Length L Ch R = 1 ,22607.91,256.515200,256.515200,256.515200
XS GIS Cut Line= 2
910386.374556264805331.997428719909808.249556264804738.247428719
#Sta/Elev= 30
9794.047119.51659817.771118.26139839.021116.05799853.355111.6059 9867.69103.7518
  9873.6101.70729887.55799.368589896.35996.390169915.47293.562059939.36393.45014
9957.34489.066239968.03289.071569985.25887.6266410027.1391.9564410041.0989.19823
10152.7589.0260710208.5891.0614710254.7289.8216310278.3690.2997810292.3289.49768
10340.7390.4800510403.98 89.922610417.9391.4443110431.8989.7014310515.6490.25628
10541.4191.1946910555.7592.5625110571.4694.7876310599.38102.029410622.76103.9023
#Mann= 3 , 0 , 0
9794.047  0.0461       09794.047  0.0461       010622.76  0.0461       0
#XS Ineff= 2 , 0
       0                               0
Bank Sta=9794.047,10622.76
Exp/Cntr=0.3,0.1