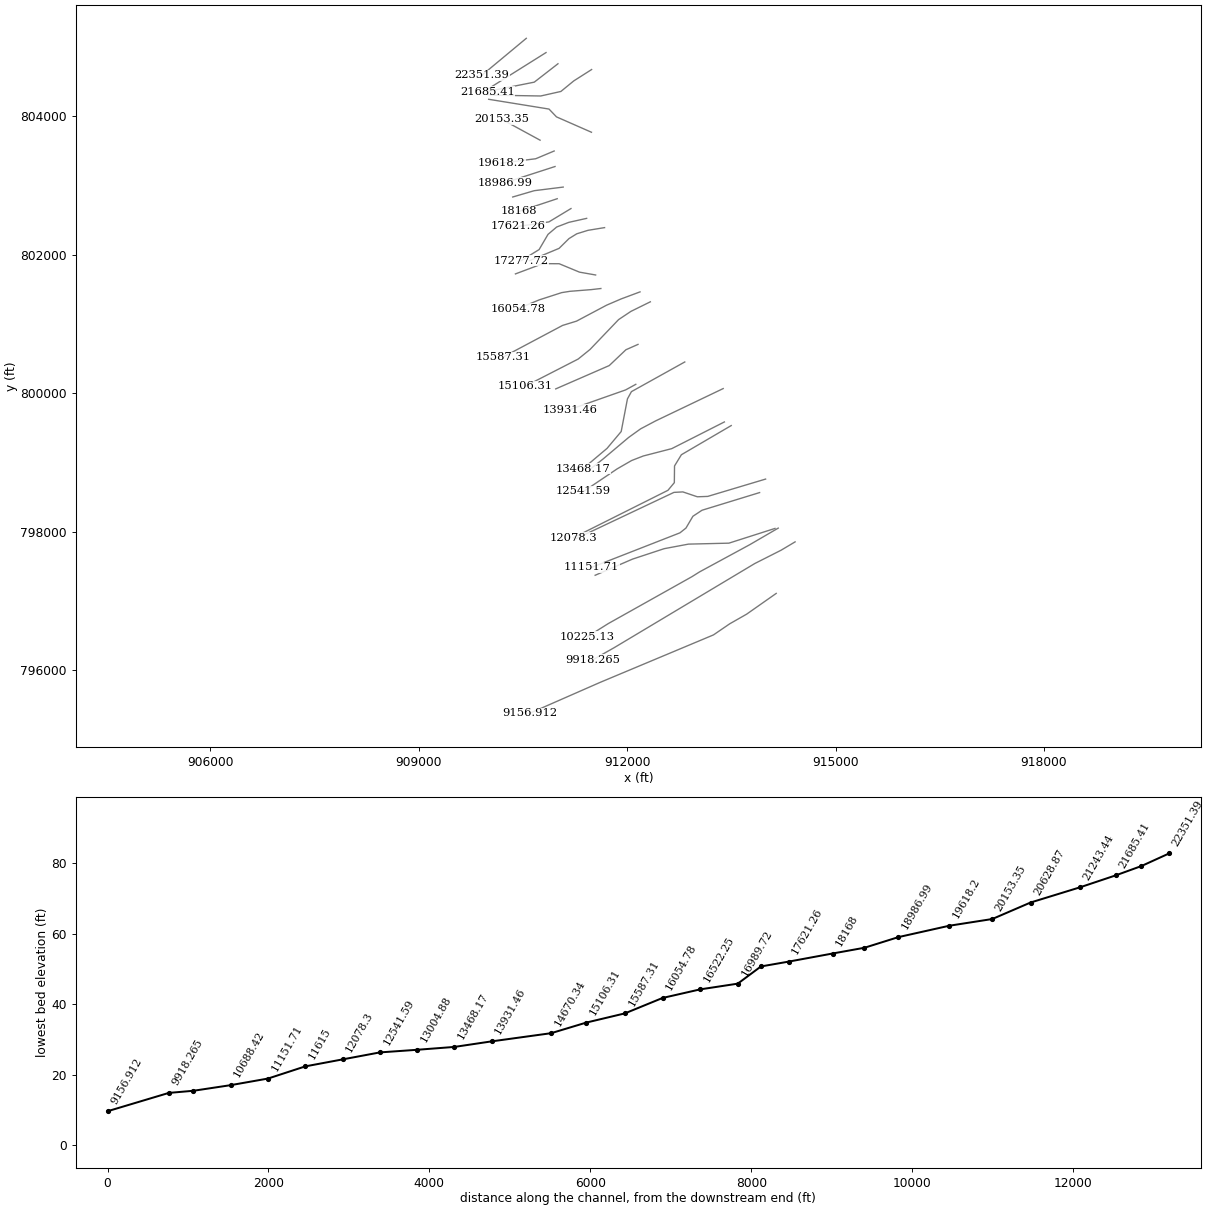
HEC-RAS study 13117_ras.prj: 13117

--- 13117_ras.g01 (geometry) --- (continued)

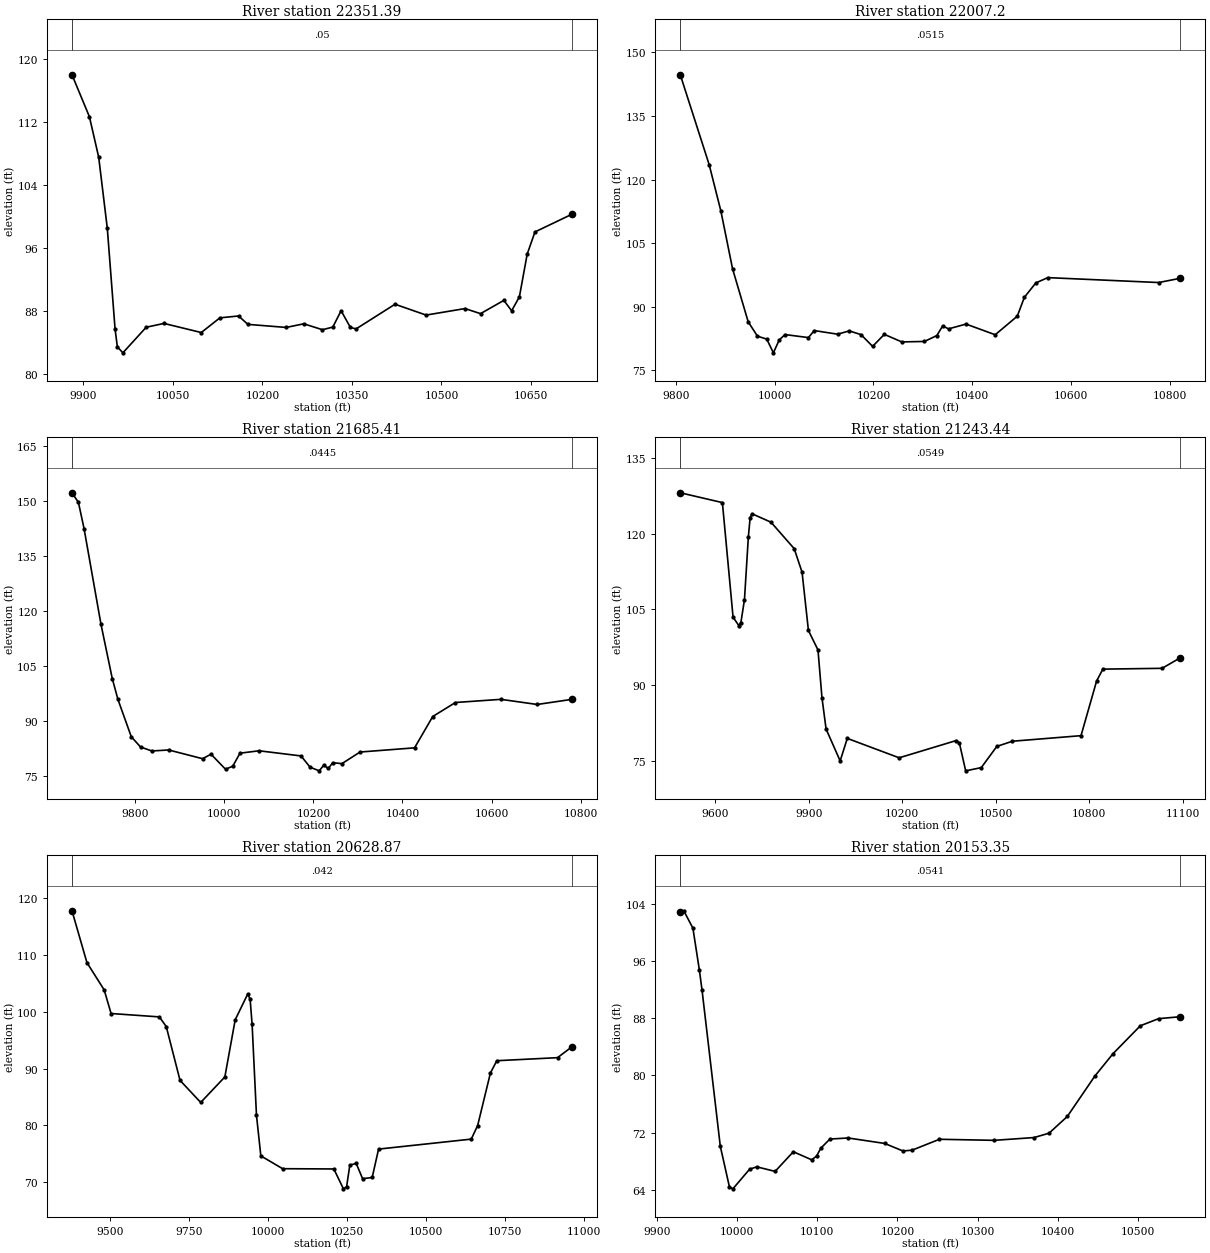
Type RM Length L Ch R = 1 ,22351.39,344.189700,344.189700,344.189700
XS GIS Cut Line= 2
910550.437056264805123.664095386909907.207889598804587.205762053
#Sta/Elev= 30
9881.181117.96599910.321112.65919925.934107.50799940.34698.487959953.36785.69839
 9957.1683.483239966.38982.7141210005.4585.9589610035.2386.4429310097.6885.28866
 10128.987.1508310160.1387.3877910175.7486.3233410239.8485.9345810269.4286.39426
10300.6585.6445610317.9785.9787110331.8788.0499510347.4985.9272810357.0385.75163
10422.1488.8764910474.2287.5012710539.3388.3265710565.3787.6835310604.4489.36337
10617.4688.0454810630.4889.81976 10643.595.2233110656.5298.0421810718.76100.2971
#Mann= 3 , 0 , 0
9881.181    0.05       09881.181    0.05       010718.76    0.05       0
#XS Ineff= 2 , 0
       0                               0
Bank Sta=9881.181,10718.76
Exp/Cntr=0.3,0.1

Type RM Length L Ch R = 1 , 22007.2,321.788800,321.788800,321.788800
XS GIS Cut Line= 2
910834.512574872804918.205622435909977.741741539804379.143122435
#Sta/Elev= 30
9809.229144.70989867.726123.50669891.356112.60599914.98598.987679946.69486.44527
9965.47183.066879984.24982.373049997.68879.13827 10009.582.1819810021.3283.44674
10068.5882.7337410080.3984.3894810127.6583.5380710151.2884.3083910174.9183.44363
10198.54 80.664610222.1783.4959210257.6181.7120210303.4781.82513 10328.583.21357
10340.3185.4853310352.1384.7895410387.5785.9203110446.6583.4053910491.2587.76912
10505.7292.2453310528.8195.6193210552.9896.8765510777.46 95.717210821.4896.72579
#Mann= 3 , 0 , 0
9809.229  0.0515       09809.229  0.0515       010821.48  0.0515       0
#XS Ineff= 2 , 0
       0                               0
Bank Sta=9809.229,10821.48
Exp/Cntr=0.3,0.1

Type RM Length L Ch R = 1 ,21685.41,441.978400,441.978400,441.978400
XS GIS Cut Line= 3
911006.387574872804756.747289102910665.241741539804491.122289102
909988.158408206804355.705622435
#Sta/Elev= 30
9657.995152.22159672.428149.61439685.102142.47159723.123116.36769748.471 101.596
9761.14595.933839791.05785.78381 9811.84 82.97689837.18781.887679875.20982.15612
9951.25279.777639970.10681.0099510002.6676.9144210018.9477.7327410035.2181.28579
10077.9981.9390710172.1980.5358110192.5877.4674210212.9876.4751310223.1878.00152
10233.3877.1379710243.5778.6964610263.9778.4337410304.7681.6000310427.1482.73961
10467.9391.2746710518.9295.09048 10620.9 95.951310702.4994.5550210780.8595.95783
#Mann= 3 , 0 , 0
9657.995  0.0445       09657.995  0.0445       010780.85  0.0445       0
#XS Ineff= 2 , 0
       0                               0
Bank Sta=9657.995,10780.85
Exp/Cntr=0.3,0.1

Type RM Length L Ch R = 1 ,21243.44,614.564900,614.564900,614.564900
XS GIS Cut Line= 6
911490.596679094804673.221741959911233.942879593804509.365427305
911048.267411771 804356.85401291910758.123685984804291.469511324
910118.604144155804302.495710321909996.404935984804311.000761324
#Sta/Elev= 30
9488.013128.07469623.128126.13299657.407103.47489675.676101.83469682.501102.4172
9693.945106.92319706.399119.32239712.215123.18449718.348123.92089779.138122.2547
9853.556117.02569878.797 112.3659899.177100.84819929.85396.998799942.61787.56434
9955.82381.37169   1000175.0586510023.8879.5176210190.27   75.6810373.7179.09732
10383.7178.5597810403.7173.1032710453.7273.7391510503.7377.9358510553.7478.95702
10773.7780.0560810823.7890.8552110843.7893.2106711033.9593.3706711092.6995.46672
#Mann= 3 , 0 , 0
9488.013  0.0549       09488.013  0.0549       011092.69  0.0549       0
#XS Ineff= 2 , 0
       0                               0
Bank Sta=9488.013,11092.69
Exp/Cntr=0.3,0.1

Type RM Length L Ch R = 1 ,20628.87,475.520900,475.520900,475.520900
XS GIS Cut Line= 4
911488.387537508803767.890550831910985.112422875803989.828373633
910877.481324873804102.667427991910009.425769317804243.726455768
#Sta/Elev= 30
9378.343117.82489425.762108.67929480.408103.87049502.26699.709099655.27499.11184
9677.13397.41387 9720.8587.917829786.42584.024479862.92988.525839895.71698.59908
9935.528103.15959943.032102.24119949.34897.778089963.167 81.77169976.987 74.6045
10046.0972.3440610208.4172.29793 10238.868.7924510248.9369.1702110259.0672.97872
10279.3373.2716410299.5970.5802510329.9870.7963210350.24  75.80110644.0577.55947
10664.3179.9589310704.8489.23472 10725.191.3858410917.5991.9235710963.7693.86462
#Mann= 3 , 0 , 0
9378.343   0.042       09378.343   0.042       010963.76   0.042       0
#XS Ineff= 2 , 0
       0                               0
Bank Sta=9378.343,10963.76
Exp/Cntr=0.3,0.1

Type RM Length L Ch R = 1 ,20153.35,535.153400,535.153400,535.153400
XS GIS Cut Line= 2
910748.840494029 803653.55352121910201.109605644803952.533263778
#Sta/Elev= 30
9929.014102.88459933.389103.02819944.782100.59099952.90494.685449956.17591.91556
 9978.9670.072269990.353 64.38059994.648 64.117210015.5266.8665210024.5367.19577
10047.3266.55795 10070.169.3077810092.8968.1834110099.0168.6875610104.2869.79421
10115.6771.0847310138.46 71.233310184.0370.4707810206.8269.4163610218.2169.52778
10252.3971.0529610320.7470.9043510370.3471.29306 10389.171.9020410411.8974.24057
10446.0679.8627610468.8583.0206910503.03 86.936210525.8187.9308410553.0388.20404
#Mann= 3 , 0 , 0
9929.014  0.0541       09929.014  0.0541       010553.03  0.0541       0
#XS Ineff= 2 , 0
       0                               0
Bank Sta=9929.014,10553.03
Exp/Cntr=0.3,0.1

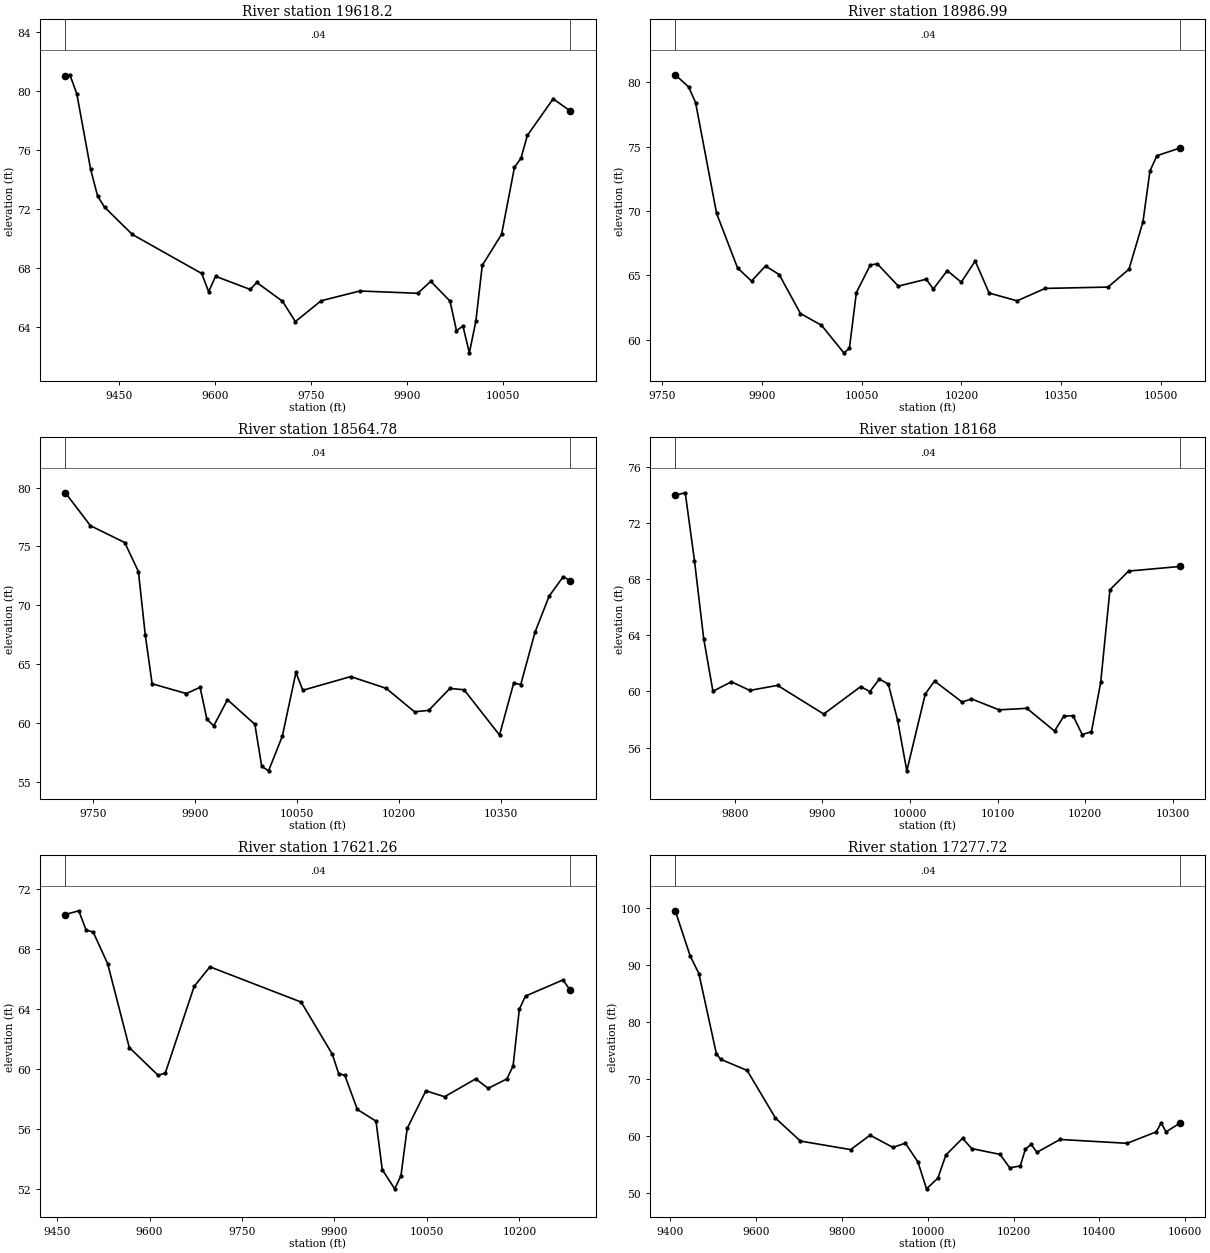
Type RM Length L Ch R = 1 , 19618.2,631.208300,631.208300,631.208300
XS GIS Cut Line= 3
910951.478722931803497.362012053910685.853722931803385.382845386
910188.457889598803322.882845386
#Sta/Elev= 30
9366.14681.032439373.17681.122159384.02979.831279405.73374.685139416.58672.87039
9427.43872.119149470.84770.26188 9579.3767.607229590.22266.368519601.07467.41445
 9655.2766.520639665.34866.996529705.66365.71936 9725.8264.335049766.13565.75065
9826.60766.415729917.31466.259289937.47267.074289967.70765.729069977.78663.71082
9987.86564.036679997.94362.2088810008.0264.34229 10018.168.1551810048.3470.27541
10068.4974.8360610078.5775.4381210088.6576.9986710128.9779.4852910155.7278.66032
#Mann= 3 , 0 , 0
9366.146    0.04       09366.146    0.04       010155.72    0.04       0
#XS Ineff= 2 , 0
       09642.298                       0
Bank Sta=9366.146,10155.72
Exp/Cntr=0.3,0.1

Type RM Length L Ch R = 1 ,18986.99,422.207600,422.207600,422.207600
XS GIS Cut Line= 2
910964.105908678803273.251288663910241.770850633 803038.85117049
#Sta/Elev= 30
9769.53880.568029789.62579.625539800.13878.404269831.67869.819249863.21865.58275
9884.24564.555769905.27265.730439925.86465.065789957.838 62.03959989.37861.13241
10023.0658.9895810031.4359.3288210041.9563.6677110062.9765.8100710073.4965.89515
10105.0364.1661910147.0864.7044510157.5963.9367210178.6265.3710310199.6564.47371
10220.6766.11167 10241.763.6264610283.7563.0260910325.8163.9889710420.4364.09296
10451.9765.4799310472.99 69.152710483.5173.1080810494.0274.2886910528.9574.89086
#Mann= 3 , 0 , 0
9769.538    0.04       09769.538    0.04       010528.95    0.04       0
#XS Ineff= 2 , 0
       0                               0
Bank Sta=9769.538,10528.95
Exp/Cntr=0.3,0.1

Type RM Length L Ch R = 1 ,18564.78,396.784000,396.784000,396.784000
XS GIS Cut Line= 3
911081.687056265802976.528678719910665.020389598802924.445345386
910355.124556265802833.299512053
#Sta/Elev= 30
9709.40479.555949746.37776.760999796.76675.334499816.92172.869379826.99967.49017
9837.07763.355819887.46662.525239907.62263.05532  9917.760.345569927.777 59.7868
9947.93362.002999988.24459.916599998.32256.35249 10008.455.9705610028.5658.89372
10048.7164.3138710058.7962.8060710129.3363.9655210181.4562.9680910223.1560.97765
10243.9961.0994310275.2662.9619310296.1162.8450110348.23 59.007410369.0863.40672
 10379.563.2933110400.3567.7091910421.1970.7863710442.0472.4451810452.3372.08875
#Mann= 3 , 0 , 0
9709.404    0.04       09709.404    0.04       010452.33    0.04       0
#XS Ineff= 2 , 0
       0                               0
Bank Sta=9709.404,10452.33
Exp/Cntr=0.3,0.1

Type RM Length L Ch R = 1 ,   18168,546.737100,546.737100,546.737100
XS GIS Cut Line= 2
 910995.81166991802808.679082146 910448.93666991802626.387415479
#Sta/Elev= 30
 9732.04 73.98979743.43674.165239753.97769.328899764.51863.766159775.05960.01355
9796.14160.684369817.22360.072239848.84660.43199 9901.5558.386889943.71460.34305
9954.25559.988879965.034 60.88529975.33760.516419985.87857.950439996.41954.33735
 10017.559.8205110028.0460.7406110059.6659.23513 10070.259.4683310101.8358.68575
10133.4558.7964110165.0757.1753110175.6158.2315810186.1658.27195 10196.756.92044
10207.2457.1333510217.7860.6565810228.3267.2477410249.6468.58178 10308.568.91354
#Mann= 3 , 0 , 0
 9732.04    0.04       0 9732.04    0.04       0 10308.5    0.04       0
#XS Ineff= 2 , 0
       0                               0
Bank Sta=9732.04,10308.5
Exp/Cntr=0.3,0.1

Type RM Length L Ch R = 1 ,17621.26,343.542200,343.542200,343.542200
XS GIS Cut Line= 3
911193.666222931802666.632845386910875.957889598802473.924512052
910433.249556265802408.820345386
#Sta/Elev= 30
9463.40670.288199485.23770.537059496.93369.264629508.62969.11271 9532.0267.01641
9567.10861.439239613.89159.587519625.58759.74513 9672.3765.506279697.94166.80633
9846.06664.459489896.60460.980419906.71159.699839916.81959.581769937.03457.31826
9967.35756.538259977.464 53.31379997.679  52.03510007.7952.9058910017.8956.05168
10048.2258.5598810078.5458.1638610129.0859.3523510149.2958.7224810179.6259.35032
10189.7260.2081610199.8363.9931110209.9464.8649510270.5865.9326710282.4665.25365
#Mann= 3 , 0 , 0
9463.406    0.04       09463.406    0.04       010282.46    0.04       0
#XS Ineff= 2 , 0
       09754.471        10269.62       0
Bank Sta=9463.406,10282.46
Exp/Cntr=0.3,0.1

Type RM Length L Ch R = 1 ,17277.72,288.000000,288.000000,288.000000
XS GIS Cut Line= 6
911419.099436423802524.961818414911162.939978441802467.514430704
910987.710877588802400.033736562910863.234992239802294.054260059
910735.018095809802074.483318404910475.606451724801913.951400111
#Sta/Elev= 30
9411.274 99.5068 9446.03 91.57989466.416 88.47459507.18774.382679517.37973.41316
9578.83871.469589644.96863.08889 9703.0959.063319820.193 57.55859865.53960.08851
9918.84857.947459947.77158.693379977.11455.393879997.11550.6691810023.5652.54321
10042.3656.6103110081.0759.5426210102.7357.7358310168.6456.7169510191.35 54.3468
10215.6654.6993510227.8257.6574710241.01 58.468210254.6457.0900510308.5259.34108
10464.8958.6665810532.9960.6851210544.25 62.2581 10555.560.6710710588.5862.23156
#Mann= 3 , 0 , 0
9411.274    0.04       09411.274    0.04       010588.58    0.04       0
#XS Ineff= 2 , 0
       09919.754        10533.36       0
Bank Sta=9411.274,10588.58
Exp/Cntr=0.3,0.1

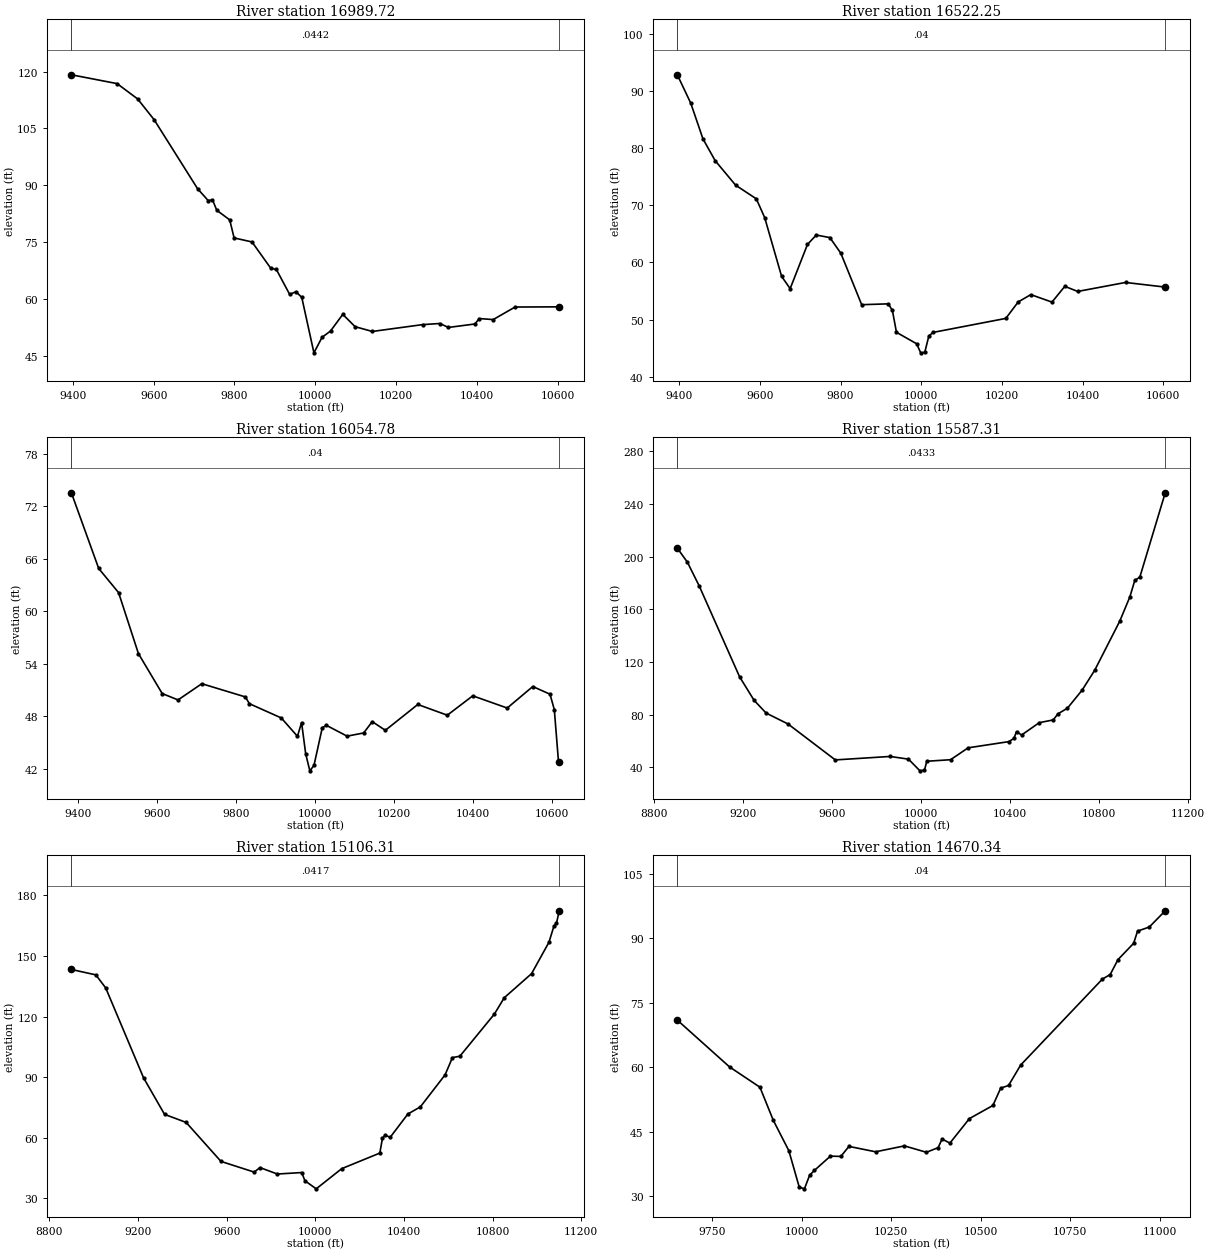
Type RM Length L Ch R = 1 ,16989.72,467.469800,467.469800,467.469800
XS GIS Cut Line= 6
911677.026352229802391.374544044911438.907295509802352.461084761
911276.855581832802302.114578311911164.801930816 802232.86891644
911022.498153656802091.942697527910596.500862759801913.916460212
#Sta/Elev= 30
9396.523119.14819509.594116.81969560.382112.77949601.108107.31249708.86289.06625
9734.99385.949939745.57786.167179756.16183.403419788.207 80.86419799.01576.10527
9843.32875.047129889.99768.065929903.43267.811829936.483 61.20999951.84461.90637
9966.35660.442879996.48945.7925410016.6249.8947110037.4851.5381910067.8455.94361
10098.3152.6941810140.8551.4346110265.1153.23384 10307.8 53.532610329.2152.49257
10394.5353.4048710405.52 54.835710439.8954.5667810494.0457.8785510603.4157.92962
#Mann= 3 , 0 , 0
9396.523  0.0442       09396.523  0.0442       010603.41  0.0442       0
#XS Ineff= 2 , 0
       0                               0
Bank Sta=9396.523,10603.41
Exp/Cntr=0.3,0.1

Type RM Length L Ch R = 1 ,16522.25,467.469800,467.469800,467.469800
XS GIS Cut Line= 6
911548.231065779801707.540072366911315.676525193801748.672342213
911023.628386547801870.127091806910853.932845933801871.040636734
 910744.62748795801855.000166081910394.411351675801723.264563649
#Sta/Elev= 30
9395.19292.804019428.55987.832649458.704 81.60589489.04177.780599539.78973.49073
9591.05971.109749611.81167.820849653.76757.542329674.95755.401329717.96563.13959
9739.74564.772759773.36564.330049800.61261.592239852.29552.59054 9918.2552.73954
9928.45851.582929938.52547.759059988.62845.754289998.63744.1703510008.6644.25497
10018.6747.0651810028.6847.7361410209.6250.1926110240.3953.0713710271.5854.35436
10324.0853.04325 10355.955.8015310387.8554.9095110506.5356.4805210604.9355.66849
#Mann= 3 , 0 , 0
9395.192    0.04       09395.192    0.04       010604.93    0.04       0
#XS Ineff= 2 , 0
       09581.489        10431.04       0
Bank Sta=9395.192,10604.93
Exp/Cntr=0.3,0.1

Type RM Length L Ch R = 1 ,16054.78,467.469800,467.469800,467.469800
XS GIS Cut Line= 6
911623.755229888801512.359441254911483.777423274801496.223668214
911178.172561763801471.883615134911059.505139557801452.920118527
910735.358416891801347.849702432910433.427532944801222.542923342
#Sta/Elev= 30
9382.28973.56896  9451.564.901289501.83162.139349552.06255.155869612.25250.58308
9652.37949.853239712.56951.709179822.91750.195129832.96649.42311 9913.8447.78796
 9954.7145.688159965.16847.259429975.626 43.67329986.08441.734119996.54342.35253
10017.5446.6626410028.0246.9434110080.4245.7052310122.3546.0710510144.1547.36943
10177.2846.3716410259.4249.3321410334.1548.1036710398.6250.3226910485.8548.92471
10550.6351.3862610594.2250.5082910605.1248.7405510616.0242.5978510617.74 42.7255
#Mann= 3 , 0 , 0
9382.289    0.04       09382.289    0.04       010617.74    0.04       0
#XS Ineff= 2 , 0
       09789.867        10246.26       0
Bank Sta=9382.289,10617.74
Exp/Cntr=0.3,0.1

Type RM Length L Ch R = 1 ,15587.31,481.000000,481.000000,481.000000
XS GIS Cut Line= 6
912187.313983605801463.754171357911916.613706097801362.537386374
911705.970102986801271.782559511911273.480872965801041.549868837
911072.592493146800979.479028734910213.884229925800521.655985803
#Sta/Elev= 30
8903.666206.3304 8948.68195.7905 9001.87177.74559183.694108.67659248.57490.90677
9302.71481.214599401.21572.928039613.634 45.65729859.84448.283959942.38646.24165
9994.10637.3669910014.4437.8485810024.6244.6397610131.7745.81452 10210.754.84303
10393.6759.5352810416.5462.0153810427.9767.1607910450.8264.54959 10530.473.92938
10593.0475.9995510614.0780.5932610657.09 84.950410722.8798.6091310779.27113.6428
10892.09150.967410937.21169.270510959.55181.831210982.34184.442811096.41248.3765
#Mann= 3 , 0 , 0
8903.666  0.0433       08903.666  0.0433       011096.41  0.0433       0
#XS Ineff= 2 , 0
       0 9833.74                       0
Bank Sta=8903.666,11096.41
Exp/Cntr=0.3,0.1

Type RM Length L Ch R = 1 ,15106.31,435.968000,435.968000,435.968000
XS GIS Cut Line= 6
912335.622387291 801320.54615351912056.461879204801182.462873116
911878.752992557801063.620553936 911467.51779463800632.344342131
911297.431161509800494.364941254910533.461016289800101.094969771
#Sta/Elev= 30
8899.291143.27089009.613140.60099054.091134.16519224.999 89.67059319.51971.61322
9417.09367.601659574.26748.32273 9724.1343.036649750.27545.264359828.71142.08182
9938.50342.810029953.11538.7472410003.9234.7531110119.0944.7385210290.9352.44105
10302.6859.6671310314.4361.2655410337.9360.2795210417.6771.7782710473.8875.30438
10585.2591.1138610618.6699.6759210652.07100.353310807.99121.235310852.54129.3012
10975.68 141.20711054.17156.7553 11076.6164.743911087.81166.102711100.75172.3042
#Mann= 3 , 0 , 0
8899.291  0.0417       08899.291  0.0417       011100.75  0.0417       0
#XS Ineff= 2 , 0
       09776.253                       0
Bank Sta=8899.291,11100.75
Exp/Cntr=0.3,0.1

Type RM Length L Ch R = 1 ,14670.34,738.878100,738.878100,738.878100
XS GIS Cut Line= 4
912158.176757775800705.663435004911984.062304644800628.279233612
 911744.17128033800399.995839507910974.198476483800063.374563453
#Sta/Elev= 30
9653.17670.978439798.914 60.10179883.83155.37682    992147.698789964.51940.61673
9993.53132.1483410008.0431.7521410022.5434.9258210035.6836.0221610080.5739.36109
10109.5839.2870910132.3141.61743 10206.740.3640410287.19 41.738510348.5840.24618
10381.3241.3325110392.2443.3360410414.0642.3800510468.6348.0867210534.1251.13399
10555.9555.1726610577.7755.7801710611.7260.5392810839.7180.5125210861.5381.57471
10883.3685.0485410927.0288.8428210937.9391.6738310970.6792.61943 11015.2 96.3988
#Mann= 3 , 0 , 0
9653.176    0.04       09653.176    0.04       0 11015.2    0.04       0
#XS Ineff= 2 , 0
       0                               0
Bank Sta=9653.176,11015.2
Exp/Cntr=0.3,0.1

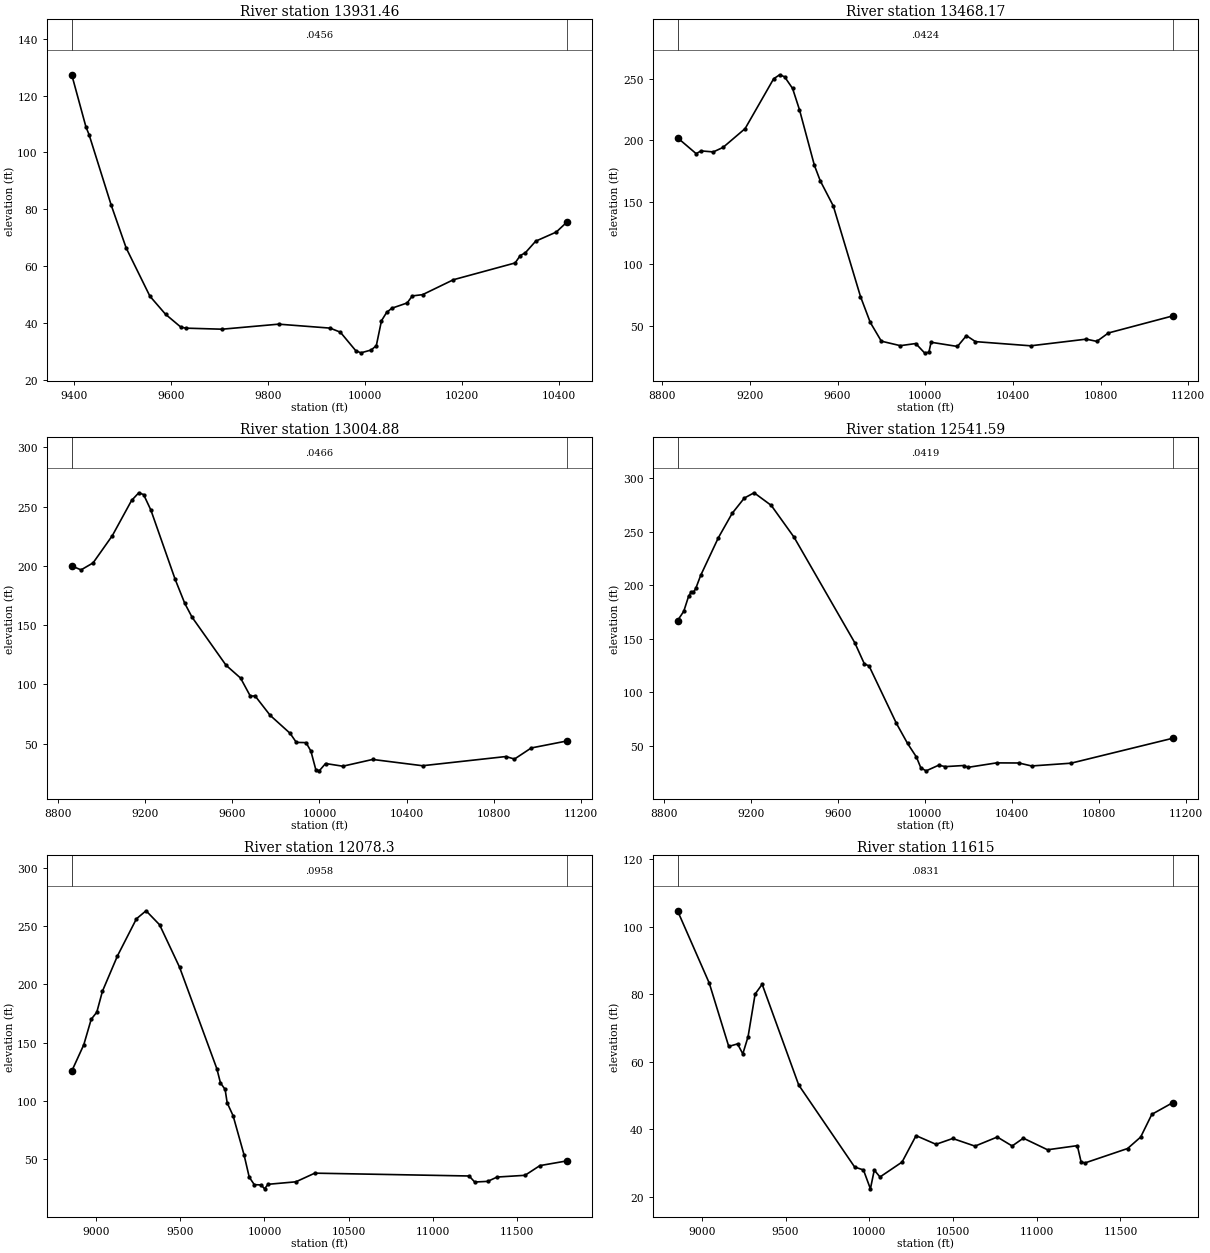
Type RM Length L Ch R = 1 ,13931.46,463.291300,463.291300,463.291300
XS GIS Cut Line= 3
912126.210456812 800129.17258989 911979.72420648800048.508023412
911173.726149926799764.038121099
#Sta/Elev= 30
9394.518127.32429423.899108.90669430.147106.29679475.81181.483889506.82466.32942
9555.72249.375729587.96443.016619619.77838.455399630.38238.121529704.61437.75507
9821.26539.52891 9927.3138.138769948.51936.713459980.33330.191979990.93829.43294
10012.1530.4356210022.7531.9605610033.3640.7206110043.9643.6455710054.5645.12781
10086.3846.9970510096.98 49.474410118.1949.9137910181.8255.1738510309.0761.07851
10319.6863.6809110330.2864.6823910351.4968.7444410393.9171.9487310416.4775.56127
#Mann= 3 , 0 , 0
9394.518  0.0456       09394.518  0.0456       010416.47  0.0456       0
#XS Ineff= 2 , 0
       0                               0
Bank Sta=9394.518,10416.47
Exp/Cntr=0.3,0.1

Type RM Length L Ch R = 1 ,13468.17,463.291400,463.291400,463.291400
XS GIS Cut Line= 6
912831.074978569800452.037435855912063.439894971800023.649949041
912006.056344133799918.995287082911916.082481762799447.737269364
911712.777943207  799204.8715761911366.447238313798911.608368099
#Sta/Elev= 30
8869.713202.07368954.696189.21828977.038191.44469032.893190.62699077.578194.3047
9178.117209.52769308.263249.87939335.612253.11999358.129251.49369394.627242.0504
9426.135224.77759494.256179.70599521.044167.1844  9580.4146.83539704.499 73.4704
 9749.0452.533159799.57737.313869886.10133.665399956.57835.396539996.58427.85839
10016.5828.2894910026.5836.4297110146.9533.0298410187.8141.8009610229.2436.93843
10480.97 33.556710734.5638.9495810782.6737.1408210835.7543.95668 11130.3  57.826
#Mann= 3 , 0 , 0
8869.713  0.0424       08869.713  0.0424       0 11130.3  0.0424       0
#XS Ineff= 2 , 0
       0                10870.96       0
Bank Sta=8869.713,11130.3
Exp/Cntr=0.3,0.1

Type RM Length L Ch R = 1 ,13004.88,463.291300,463.291300,463.291300
XS GIS Cut Line= 6
913383.777541035800068.000279989912407.714068914799599.389155145
912195.313316469799486.296021288912025.220004951799363.895899893
911650.881151677799047.784893516911454.894163785798893.615252724
#Sta/Elev= 30
8863.746199.99238906.522196.68188961.677202.60099049.927225.59349138.176255.3003
9171.269261.76889193.331260.24989226.649247.1848 9337.86188.79199382.345168.3339
9415.708156.70959571.405  116.199638.132105.34429682.61690.170339704.85990.25723
9773.70773.915569865.12258.731929893.91851.060919938.40350.855669960.70643.68497
9983.04428.14844    999927.0459610027.9333.22786 10107.130.9514210243.9436.65906
10472.6631.3604710855.2639.1227110894.3736.9922110971.3246.35074 11136.252.30294
#Mann= 3 , 0 , 0
8863.746  0.0466       08863.746  0.0466       0 11136.2  0.0466       0
#XS Ineff= 2 , 0
       0                10926.69       0
Bank Sta=8863.746,11136.2
Exp/Cntr=0.3,0.1

Type RM Length L Ch R = 1 ,12541.59,463.291300,463.291300,463.291300
XS GIS Cut Line= 6
913400.820829594799586.121472283 912643.71601619799200.967982987
912234.888188151799095.059901835912066.850596976799029.770529691
911858.574724387798909.196943784911374.666747097798582.886868489
#Sta/Elev= 30
8861.193166.9556 8889.82175.63348911.993189.6916 8923.08193.29898934.166193.3298
8945.253 197.1768967.427209.18129048.853 244.5059112.137267.27669168.104281.6253
9213.189286.57869292.087274.74239396.852244.97559676.131146.16749720.153 126.387
9741.611124.49929867.49870.683229918.70251.908949959.43839.197559979.80629.01584
10004.2326.3013610061.5731.5668410092.5230.2526210175.9731.2799310197.0629.58447
10327.7933.7495710430.1833.6473510488.8930.8630710669.9633.4588711138.7956.85676
#Mann= 3 , 0 , 0
8861.193  0.0419       08861.193  0.0419       011138.79  0.0419       0
#XS Ineff= 2 , 0
       0                10596.06       0
Bank Sta=8861.193,11138.79
Exp/Cntr=0.3,0.1

Type RM Length L Ch R = 1 , 12078.3,463.291400,463.291400,463.291400
XS GIS Cut Line= 6
913499.584923238799534.092789456912782.129666001799112.908662558
912683.620467156798951.087231129912680.861330032798709.914833918
 912588.98880294798599.414692745911228.449744791797915.417286351
#Sta/Elev= 30
8856.476125.49448927.815148.08848971.998170.01389005.135176.09629038.506194.0471
9127.743224.44879240.381256.33359297.569263.22849377.958251.17939496.379214.7576
9717.833127.49299739.139115.33119766.839109.73839779.03798.224259814.22287.12601
9879.32953.48576 9909.9434.371179940.09427.904699980.37127.66581   10001 24.3214
10021.2328.2088710187.0530.3640510299.1137.7943611215.2135.3615611248.3730.18069
11325.7630.7400911381.0434.4490411546.8735.9424611635.32 44.279111797.3348.37143
#Mann= 3 , 0 , 0
8856.476  0.0958       08856.476  0.0958       011797.33  0.0958       0
#XS Ineff= 2 , 0
       0                10327.51       0
Bank Sta=8856.476,11797.33
Exp/Cntr=0.3,0.1

Type RM Length L Ch R = 1 ,   11615,463.291300,463.291300,463.291300
XS GIS Cut Line= 6
913994.051829159798761.516732231913161.248249233798511.331962258
913011.650166035798505.949984103912803.562082648798576.287472785
912675.167677134798569.454105884911241.491444826797889.333886221
#Sta/Elev= 30
8855.015 104.7329044.41783.305299160.77564.536259213.30565.289989244.80562.34153
9276.30667.440849318.307 80.05259360.30982.953219578.67653.101979912.758 28.7938
9965.19527.9412310006.7422.3423610029.8427.9029410063.9325.85436 10195.730.27339
10279.3538.1064110398.4535.5337910498.2937.2584610631.3134.9955110764.3437.69544
10853.2235.0436810919.9537.3557411064.5233.9192111242.4735.1408111264.7130.35776
11286.9529.9967711542.7534.29341 11620.6 37.687511687.32 44.418511813.5647.91452
#Mann= 3 , 0 , 0
8855.015  0.0831       08855.015  0.0831       011813.56  0.0831       0
#XS Ineff= 2 , 0
       0                 10332.1       0
Bank Sta=8855.015,11813.56
Exp/Cntr=0.3,0.1

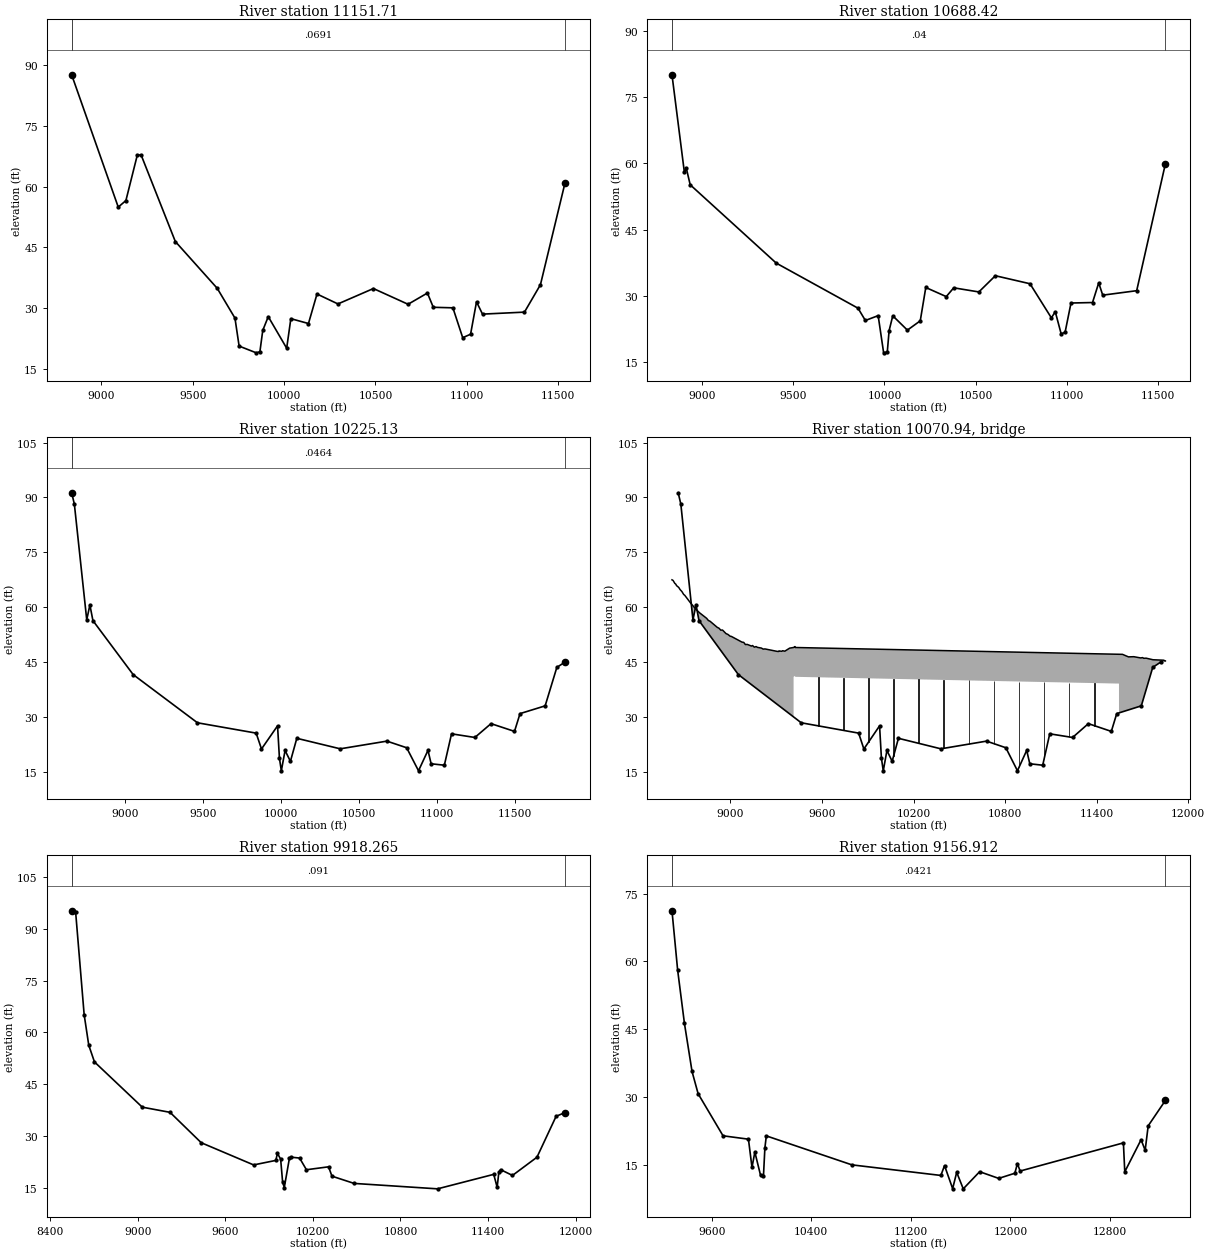
Type RM Length L Ch R = 1 ,11151.71,463.291400,463.291400,463.291400
XS GIS Cut Line= 6
913907.896376431 798566.62482819913079.284675777798311.691530049
912948.077591568798224.744531989 912848.25060901798054.422032997
912761.563714743797985.512245014 911491.89208585797487.649524599
#Sta/Elev= 30
8837.10187.664019092.15554.941559134.02456.54531 9196.6567.824479217.44567.82403
9404.59846.428969634.01834.854199731.14527.478739753.84720.564589847.82518.89289
9867.61619.167369883.342 24.45099913.39927.8431310014.24 20.037110037.0627.34284
10133.5326.14322 10180.233.4418110294.8830.98777   1048934.7954310678.7230.90568
10784.7233.6848110816.7930.1559310924.1630.0271310977.8422.6420211020.8823.49216
11053.4631.5165111086.2528.46783 11315.928.9619911403.3835.74253   1153860.94158
#Mann= 3 , 0 , 0
8837.101  0.0691       08837.101  0.0691       0   11538  0.0691       0
#XS Ineff= 2 , 0
       0                10307.77       0
Bank Sta=8837.101,11538
Exp/Cntr=0.3,0.1

Type RM Length L Ch R = 1 ,10688.42,463.291300,463.291300,463.291300
XS GIS Cut Line= 6
914128.864592075798048.995537847 913466.03450951797836.535385713
912884.110832065797822.629314378912534.224491745797756.788342237
912078.367660135797605.965369716911541.450546026797372.882564127
#Sta/Elev= 30
8836.17680.095998904.13657.952998914.77758.85543 8936.0655.14202 9407.28 37.3792
 9855.3927.147679895.47524.363499965.624 25.46269995.62517.0246210015.6417.22633
10025.6522.0750110045.67 25.426110125.7722.1737510196.2124.2854110226.5131.84664
10338.6229.7811410379.5931.7722710517.2330.8381910607.6234.5139210797.3532.69735
10914.5224.9583910935.8226.3564910967.9721.3438810989.5621.6739311021.95 28.3246
11139.8928.4351711173.8932.8959511195.7830.1061311381.8231.1216911538.9259.87799
#Mann= 3 , 0 , 0
8836.176    0.04       08836.176    0.04       011538.92    0.04       0
#XS Ineff= 2 , 0
       0                10370.75       0
Bank Sta=8836.176,11538.92
Exp/Cntr=0.3,0.1

Type RM Length L Ch R = 1 ,10225.13,306.865200,306.865200,306.865200
XS GIS Cut Line= 6
914175.928657637798053.746572692913767.458735271797815.294235813
913043.704229991797421.590731189 912934.06685759797352.560510095
911729.905845551796675.458780484911431.078092209796487.043024182
#Sta/Elev= 30
8658.15691.286828675.50588.210898754.846 56.63238775.023 60.69268794.51756.40691
9052.37541.685249464.40728.537119840.46225.718079874.64821.388289977.52627.70832
9989.538 18.900910001.74 15.428510025.7320.9809210060.0418.0281510100.9924.30412
10379.0721.4370110678.1923.5335710804.7421.7302210880.7715.4497210941.4421.01477
10961.6717.3537611046.3416.9634211092.3625.5263411241.9224.5319311345.4628.30417
11495.8126.1908511531.2731.0413111692.2233.1565211767.2243.6600911819.6345.09976
#Mann= 3 , 0 , 0
8658.156  0.0464       08658.156  0.0464       011819.63  0.0464       0
#XS Ineff= 2 , 0
       0                10750.78       0
Bank Sta=8658.156,11819.63
Exp/Cntr=0.3,0.1

Type RM Length L Ch R = 3 ,10070.94,,,
BEGIN DESCRIPTION:
END DESCRIPTION:
Bridge Culvert--1,0,-1,-1, 0
Deck Dist Width WeirC Skew NumUp NumDn MinLoCord MaxHiCord MaxSubmerge Is_Ogee
97.432600,112.000000,2.6,0, 60, 60, , , 0.95, 0, 0,0,,
 8617.54 8624.49 8636.07 8642.00 8647.64 8661.85 8670.80 8682.37 8693.95 8701.54
 8740.26 8774.99 8798.14 8844.45 8856.03 8867.61 8913.91 8925.49 8937.07 8948.65
 8971.80 8983.38 8999.24 9006.53 9075.99 9087.57 9098.47 9110.72 9138.16 9145.45
 9157.03 9168.61 9177.86 9203.34 9214.92 9226.49 9307.53 9316.78 9319.11 9336.63
 9342.26 9356.47 9388.57 9414.30 9414.30 9423.27 9424.8311546.0211546.0211568.98
11608.0911642.7711688.5111700.5611708.4411723.6811768.2411839.2811847.9811849.84
   67.54   67.38   66.57   66.38   65.95   65.46   64.86   64.35   63.56   63.30
   61.17   59.50   58.55   57.04   56.45   56.22   54.58   54.34   53.81   53.84
   52.86   52.66   52.14   52.10   50.55   50.47   49.88   49.92   49.47   49.61
   49.17   49.33   49.11   48.92   48.64   48.69   48.01   48.00   48.14   48.04
   48.20   48.07   48.91   49.08   49.08   49.33   49.08   47.23   47.23   47.21
   46.52   46.57   46.23   46.32   46.13   46.17   45.74   45.61   45.41   45.41
 -932.46 -932.62 -933.43 -933.62 -934.05 -934.54 -935.14 -935.65 -936.44 -936.70
 -938.83 -940.50 -941.45 -942.96 -943.55 -943.78 -945.42 -945.66 -946.19 -946.16
 -947.14 -947.34 -947.86 -947.90 -949.45 -949.53 -950.12 -950.08 -950.53 -950.39
 -950.83 -950.67 -950.89 -951.08 -951.36 -951.31 -951.99 -952.00 -951.86 -951.96
 -951.80 -951.93 -951.09 -950.92   41.08   41.33   41.08   39.23 -952.77 -952.79
 -953.48 -953.43 -953.77 -953.68 -953.87 -953.83 -954.26 -954.39 -954.59 -954.59
 8617.54 8624.49 8636.07 8647.64 8661.85 8670.80 8682.37 8693.95 8701.54 8740.26
 8774.99 8798.14 8844.45 8856.03 8867.61 8913.91 8925.49 8937.07 8948.65 8971.80
 8983.38 8999.24 9006.53 9075.99 9087.57 9098.47 9110.72 9138.16 9145.45 9157.03
 9168.61 9177.86 9203.34 9214.92 9226.49 9307.53 9316.78 9319.11 9336.63 9342.26
 9356.47 9388.57 9396.17 9401.40 9423.27 9424.83 9471.27 9471.2711568.9811610.56
11610.5611642.7711688.5111700.5611708.4411723.6811768.2411839.2811847.9811849.84
   67.54   67.38   66.57   65.95   65.46   64.86   64.35   63.56   63.30   61.17
   59.50   58.55   57.04   56.45   56.22   54.58   54.34   53.81   53.84   52.86
   52.66   52.14   52.10   50.55   50.47   49.88   49.92   49.47   49.61   49.17
   49.33   49.11   48.92   48.64   48.69   48.01   48.00   48.14   48.04   48.20
   48.07   48.91   49.01   48.91   49.33   49.08   49.04   49.04   47.21   46.53
   46.53   46.57   46.23   46.32   46.13   46.17   45.74   45.61   45.41   45.41
 -932.46 -932.62 -933.43 -934.05 -934.54 -935.14 -935.65 -936.44 -936.70 -938.83
 -940.50 -941.45 -942.96 -943.55 -943.78 -945.42 -945.66 -946.19 -946.16 -947.14
 -947.34 -947.86 -947.90 -949.45 -949.53 -950.12 -950.08 -950.53 -950.39 -950.83
 -950.67 -950.89 -951.08 -951.36 -951.31 -951.99 -952.00 -951.86 -951.96 -951.80
 -951.93 -951.09 -950.99 -951.09 -950.67 -950.92 -950.96   41.04   39.21   38.53
 -953.47 -953.43 -953.77 -953.68 -953.87 -953.83 -954.26 -954.39 -954.59 -954.59
Pier Skew, UpSta & Num, DnSta & Num=  ,9576.58, 2 ,9634.14, 2 , 0 , 0 , 0 ,,
    4.00    4.00
 -951.05   48.95
    4.00    4.00
 -951.10   48.90
Pier Skew, UpSta & Num, DnSta & Num=  ,9740.87, 2 ,9799.01, 2 , 0 , 0 , 0 ,,
    4.00    4.00
 -951.20   48.80
    4.00    4.00
 -951.25   48.75
Pier Skew, UpSta & Num, DnSta & Num=  ,9905.16, 2 ,9963.88, 2 , 0 , 0 , 0 ,,
    4.00    4.00
 -951.34   48.66
    4.00    4.00
 -951.39   48.61
Pier Skew, UpSta & Num, DnSta & Num=  ,10069.44, 2 ,10128.74, 2 , 0 , 0 , 0 ,,
    4.00    4.00
 -951.48   48.52
    4.00    4.00
 -951.54   48.46
Pier Skew, UpSta & Num, DnSta & Num=  ,10233.73, 2 ,10293.61, 2 , 0 , 0 , 0 ,,
    4.00    4.00
 -951.63   48.37
    4.00    4.00
 -951.68   48.32
Pier Skew, UpSta & Num, DnSta & Num=  ,10398.02, 2 ,10458.48, 2 , 0 , 0 , 0 ,,
    4.00    4.00
 -951.77   48.23
    4.00    4.00
 -951.82   48.18
Pier Skew, UpSta & Num, DnSta & Num=  ,10562.30, 2 ,10623.35, 2 , 0 , 0 , 0 ,,
    4.00    4.00
 -951.91   48.09
    4.00    4.00
 -951.97   48.03
Pier Skew, UpSta & Num, DnSta & Num=  ,10726.59, 2 ,10788.22, 2 , 0 , 0 , 0 ,,
    4.00    4.00
 -952.06   47.94
    4.00    4.00
 -952.11   47.89
Pier Skew, UpSta & Num, DnSta & Num=  ,10890.88, 2 ,10953.09, 2 , 0 , 0 , 0 ,,
    4.00    4.00
 -952.20   47.80
    4.00    4.00
 -952.25   47.75
Pier Skew, UpSta & Num, DnSta & Num=  ,11055.16, 2 ,11117.96, 2 , 0 , 0 , 0 ,,
    4.00    4.00
 -952.34   47.66
    4.00    4.00
 -952.40   47.60
Pier Skew, UpSta & Num, DnSta & Num=  ,11219.45, 2 ,11282.82, 2 , 0 , 0 , 0 ,,
    4.00    4.00
 -952.48   47.52
    4.00    4.00
 -952.54   47.46
Pier Skew, UpSta & Num, DnSta & Num=  ,11383.74, 2 ,11447.69, 2 , 0 , 0 , 0 ,,
    4.00    4.00
 -952.63   47.37
    4.00    4.00
 -952.68   47.32
BR Coef=-1 , 0 , 0 ,, 0 ,,,0.8,0,1,0,
WSPro=,,,, 1 ,,,, 0 ,,,, 0 ,,,,-1 ,-1 ,-1 , 0 , 0 , 0 , 0 , 0
BC Design=,, 0 ,, 0 ,,,,,,

Type RM Length L Ch R = 1 ,9918.265,761.353300,761.353300,761.353300
XS GIS Cut Line= 5
914418.491286653797855.098579737914217.137788478797734.809476931
913838.630175542797542.598579737911814.324619986796327.320801959
911501.824619986796150.237468626
#Sta/Elev= 30
8547.94395.164118575.307   94.75 8633.5565.174348665.12756.318938704.12451.49702
9031.62938.420149221.76836.92678 9435.4828.146129794.42321.729389946.05123.03434
9957.71525.068519979.47423.380869992.706 16.887510004.3715.2014310039.3623.61644
10051.0223.9678810109.3423.71238   1015620.3382210307.62 21.182910330.9518.47904
10482.5816.38677 11054.1   14.82   1143919.0060611462.3315.2564211473.9919.65061
11485.6620.37172 11567.318.6936311735.0623.9574111866.1635.7825111927.2736.85881
#Mann= 3 , 0 , 0
8547.943   0.091       08547.943   0.091       011927.27   0.091       0
#XS Ineff= 2 , 0
       0                11305.15       0
Bank Sta=8547.943,11927.27
Exp/Cntr=0.3,0.1

Type RM Length L Ch R = 1 ,9156.912,140.831500,140.831500,140.831500
XS GIS Cut Line= 6
914146.789897764797111.174968626913721.442675542796811.695801959
913478.387119986796672.806913071913244.012119986796512.216635293
911612.067675542795826.452746404910596.442675542795379.404135293
#Sta/Elev= 30
9281.04771.215729326.514 58.08219381.07646.277529442.22635.617219491.14630.68701
9691.28721.374699895.36620.626149923.84314.370839946.87817.768419992.94812.58496
10015.9812.41424 10027.518.6787510039.0221.3562710726.8214.9359511441.3412.59474
11470.8814.7739411536.089.671776 11568.613.2894711621.319.62673111752.8913.42249
11906.1811.9401712035.6713.0795212056.4315.2230612078.12 13.569212908.0319.80756
12918.9613.3992513050.0720.5053413082.8518.1709213107.1623.5804413245.1629.19767
#Mann= 3 , 0 , 0
9281.047  0.0421       09281.047  0.0421       013245.16  0.0421       0
#XS Ineff= 2 , 0
       0                 11854.7       0
Bank Sta=9281.047,13245.16
Exp/Cntr=0.3,0.1