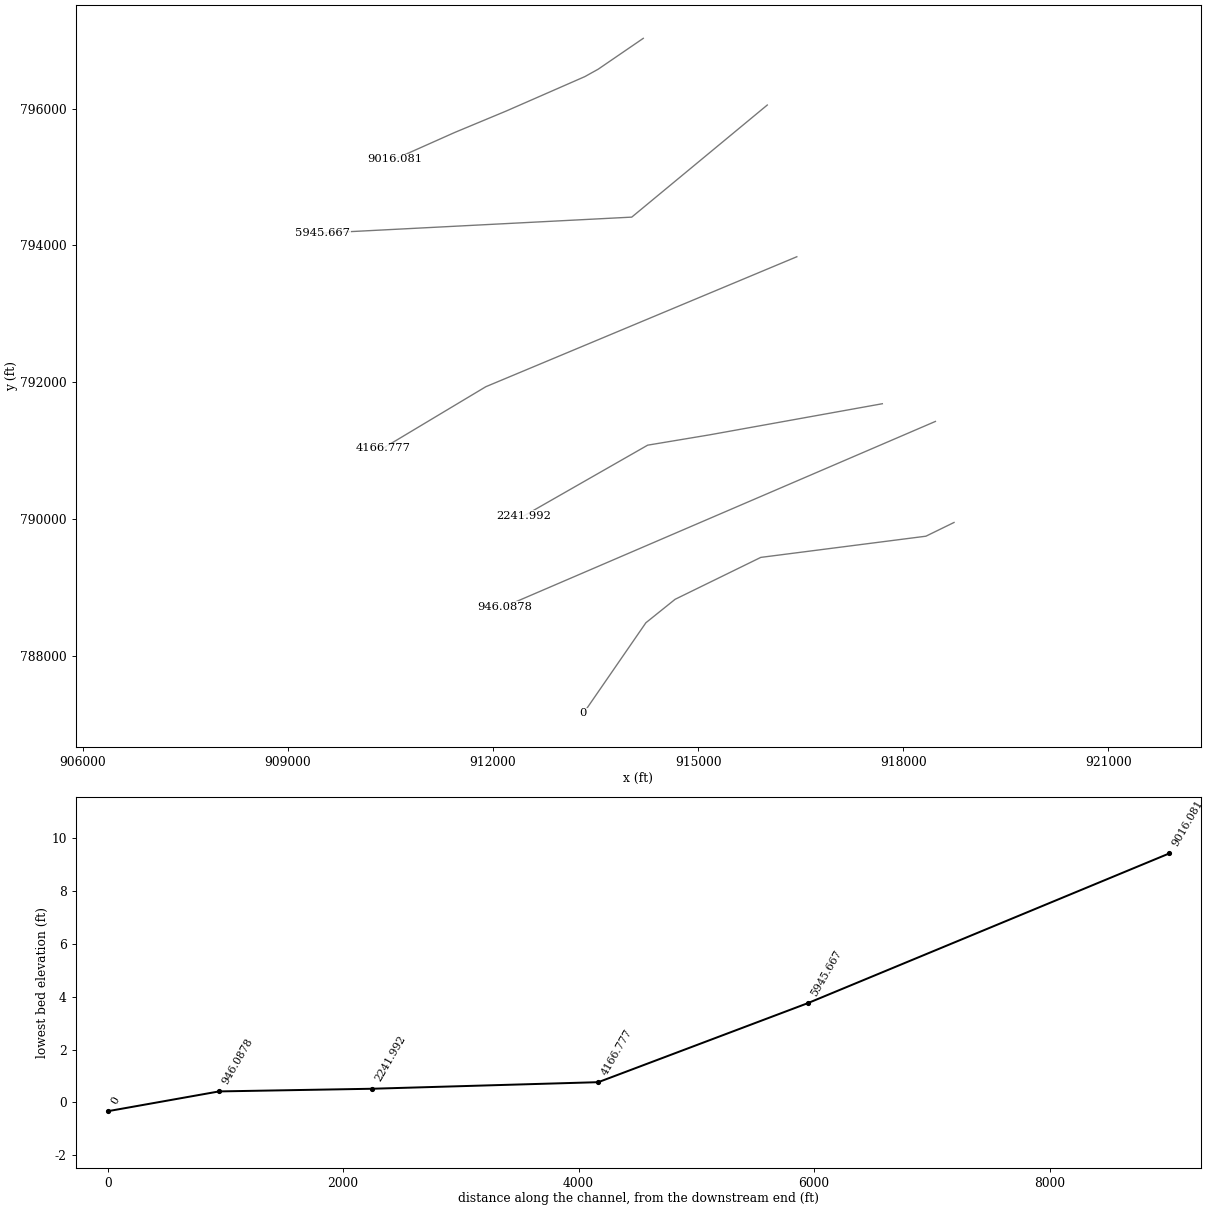
HEC-RAS study 13117_ras.prj: 13117

--- 13117_ras.g01 (geometry) --- (continued)

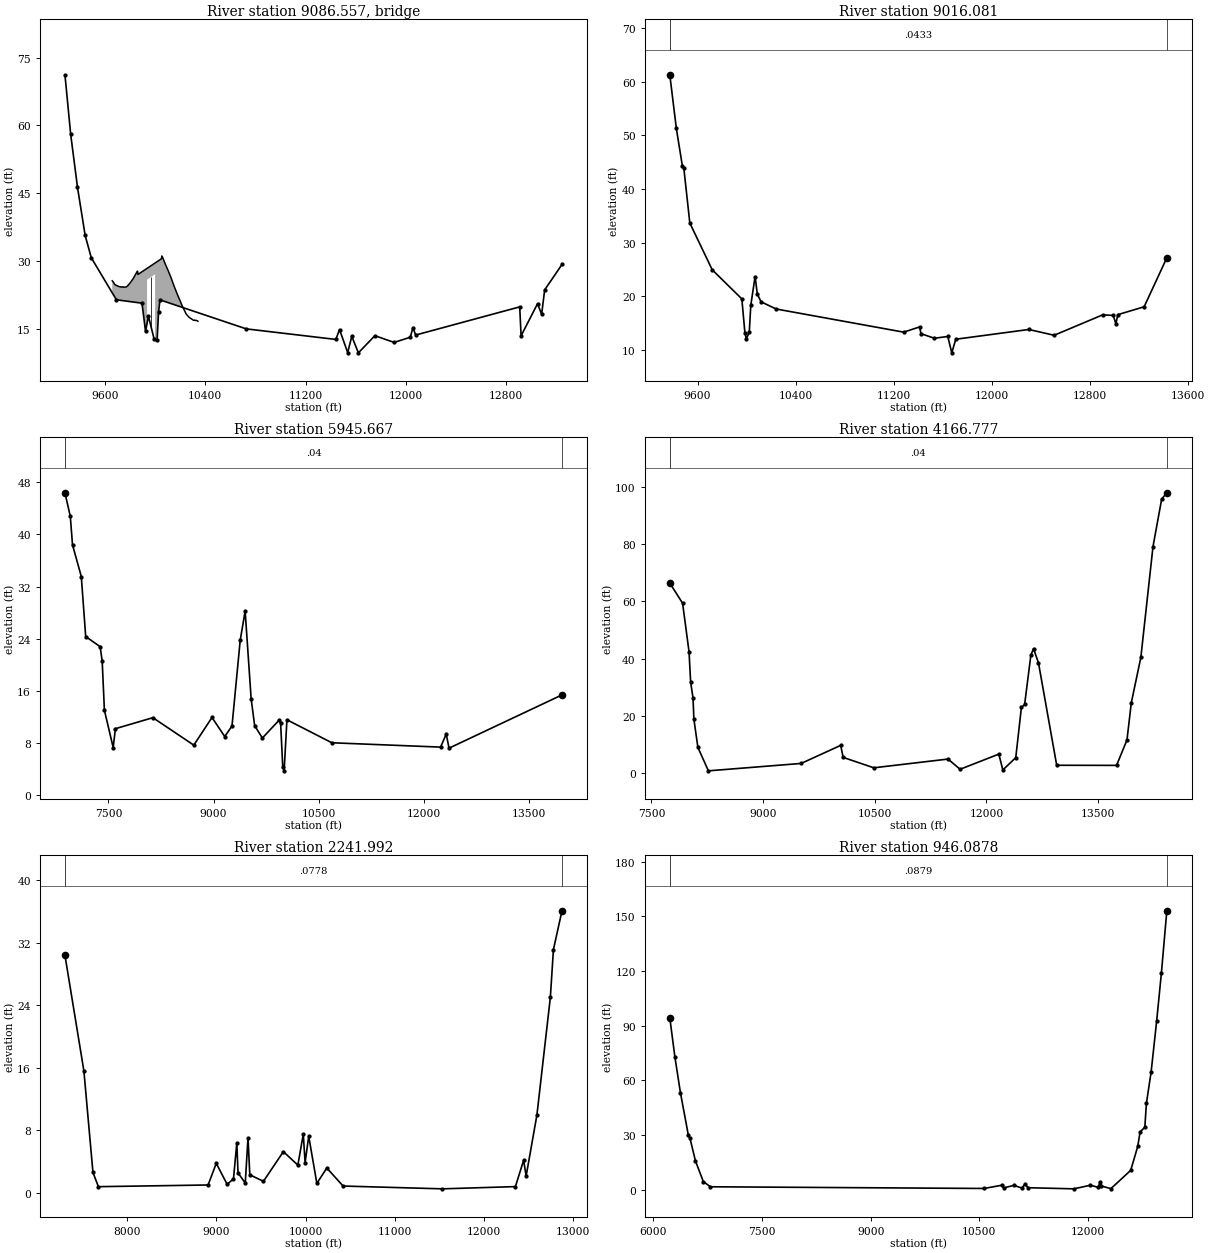
Type RM Length L Ch R = 3 ,9086.557,,,
BEGIN DESCRIPTION:
END DESCRIPTION:
Bridge Culvert--1,0,-1,-1, 0
Deck Dist Width WeirC Skew NumUp NumDn MinLoCord MaxHiCord MaxSubmerge Is_Ogee
60.245750,20.340000,2.6,0, 36, 36, , , 0.95, 0, 0,0,,
 9658.06 9668.50 9677.56 9680.89 9711.46 9730.43 9742.81 9745.35 9767.58 9779.97
 9803.89 9826.77 9858.54 9861.13 9863.30 9936.02 9936.0210000.0010000.0010050.56
10053.4910059.1710082.7510106.3410129.9210148.0210178.7010204.4310212.5710248.26
10272.1410307.9510314.7510319.8910331.8310341.56
   25.58   25.25   24.79   24.71   24.31   24.20   24.26   24.18   24.20   24.43
   25.23   26.14   27.72   27.67   26.99   28.34   28.34   29.53   29.53   30.47
   31.08   30.83   29.20   27.70   26.07   24.65   22.49   20.85   20.26   18.19
   17.47   16.81   16.89   16.80   16.80   16.63
 -974.42 -974.75 -975.21 -975.29 -975.69 -975.80 -975.74 -975.82 -975.80 -975.57
 -974.77 -973.86 -972.28 -972.33 -973.01 -971.66   25.84   27.03 -970.47 -969.53
 -968.92 -969.17 -970.80 -972.30 -973.93 -975.35 -977.51 -979.15 -979.74 -981.81
 -982.53 -983.19 -983.11 -983.20 -983.20 -983.37
 9658.06 9668.50 9677.56 9680.89 9711.46 9730.43 9742.81 9745.35 9767.58 9779.97
 9803.89 9826.77 9858.54 9861.13 9863.30 9953.09 9953.0910017.0710017.0710050.56
10053.4910059.1710082.7510106.3410129.9210148.0210178.7010204.4310212.5710248.26
10272.1410307.9510314.7510319.8910331.8310341.56
   25.58   25.25   24.79   24.71   24.31   24.20   24.26   24.18   24.20   24.43
   25.23   26.14   27.72   27.67   26.99   28.66   28.66   29.85   29.85   30.47
   31.08   30.83   29.20   27.70   26.07   24.65   22.49   20.85   20.26   18.19
   17.47   16.81   16.89   16.80   16.80   16.63
 -974.42 -974.75 -975.21 -975.29 -975.69 -975.80 -975.74 -975.82 -975.80 -975.57
 -974.77 -973.86 -972.28 -972.33 -973.01 -971.34   26.16   27.35 -970.15 -969.53
 -968.92 -969.17 -970.80 -972.30 -973.93 -975.35 -977.51 -979.15 -979.74 -981.81
 -982.53 -983.19 -983.11 -983.20 -983.20 -983.37
Pier Skew, UpSta & Num, DnSta & Num=  ,9968.01, 2 ,9985.08, 2 , 0 , 0 , 0 ,,
    3.00    3.00
 -971.06   28.94
    3.00    3.00
 -970.75   29.25
BR Coef=-1 , 0 , 0 ,, 0 ,,,0.8,0,1,0,
WSPro=,,,, 1 ,,,, 0 ,,,, 0 ,,,,-1 ,-1 ,-1 , 0 , 0 , 0 , 0 , 0
BC Design=,, 0 ,, 0 ,,,,,,

Type RM Length L Ch R = 1 ,9016.081,3070.413700,3070.413700,3070.413700
XS GIS Cut Line= 6
914198.873231098797028.709690848913539.151008875796577.320801959
913343.838508875796468.813857515912193.664897764795965.341635293
911442.796842209795652.841635293910566.060731097795262.216635293
#Sta/Elev= 30
9374.10661.332369427.60251.306219476.37544.352479488.56843.898299537.34133.66011
 9720.2424.921889961.36719.503689986.20913.214079998.22712.0315910022.2613.32937
10034.2818.2997710069.5323.6671310087.5620.3949810118.4118.9550410240.0717.62035
11280.6213.2926211410.7114.2694511421.6413.0064111530.8712.1561411640.1112.48509
11672.719.431802 11705.2 11.971112300.9313.7925912507.17 12.709612902.7716.52341
12988.8716.4135913010.7614.8318913025.6316.5540613240.66 18.027313425.6127.17229
#Mann= 3 , 0 , 0
9374.106  0.0433       09374.106  0.0433       013425.61  0.0433       0
#XS Ineff= 2 , 0
       0                12014.61       0
Bank Sta=9374.106,13425.61
Exp/Cntr=0.3,0.1

Type RM Length L Ch R = 1 ,5945.667,1778.890000,1778.890000,1778.890000
XS GIS Cut Line= 3
916011.855875851796053.661561684914030.175494187794414.724642258
909515.257629912794181.978122894
#Sta/Elev= 30
6879.68646.370936956.03942.75255 6987.4238.396627112.94633.533557175.70924.33513
7381.70522.78662 7411.0720.577267442.45113.051577567.977 7.325787599.35810.21725
8134.366 11.90398718.3277.6959738977.86511.936559159.542 9.020419263.35710.62356
9380.14923.734499450.86228.257559536.58314.806739586.64910.684219696.7958.786733
9937.11411.538549957.14111.09697 9987.18 4.4187710007.213.75820510047.2611.58401
10688.118.06030212240.177.39375512320.279.40417912360.337.23309813972.2115.39649
#Mann= 3 , 0 , 0
6879.686    0.04       06879.686    0.04       013972.21    0.04       0
#XS Ineff= 2 , 0
       09425.389        12029.47       0
Bank Sta=6879.686,13972.21
Exp/Cntr=0.3,0.1

Type RM Length L Ch R = 1 ,4166.777,1924.784400,1924.784400,1924.784400
XS GIS Cut Line= 3
916443.593354119793835.385610415911897.068915017791935.345546312
910395.697971507 791036.21944455
#Sta/Elev= 30
7747.14366.356247919.02859.331728005.733 42.33488027.40931.683488059.35226.25072
8070.76218.827868124.9528.9255198265.8480.765066 9511.663.348569 10043.39.666008
10075.815.46735610487.661.82599911484.774.87949111647.341.31371612167.576.601143
12221.761.07214612395.175.37969812471.0422.9159112514.3923.9598312597.8241.11535
12633.6143.4667712700.4538.4799112945.222.71241813749.492.67085813889.3711.55065
13947.6524.5464314075.8640.4176514239.0579.1201214355.6195.7225814424.7397.91029
#Mann= 3 , 0 , 0
7747.143    0.04       07747.143    0.04       014424.73    0.04       0
#XS Ineff= 2 , 0
       09906.762        11972.39       0
Bank Sta=7747.143,14424.73
Exp/Cntr=0.3,0.1

Type RM Length L Ch R = 1 ,2241.992,1295.904700,1295.904700,1295.904700
XS GIS Cut Line= 4
917693.791141421791686.388017838915161.301658248 791230.26760017
914262.676357767791080.496716756 912451.81022195790045.716067718
#Sta/Elev= 30
7304.24730.395087516.39815.608857618.0072.6177687678.9720.7926028908.4411.009105
8999.889 3.78198 9121.821.0911879192.9461.7927589230.2136.4165299243.7512.551529
9325.0381.2563939355.5217.0536859375.8422.3149299528.2561.4767379751.7965.276085
9914.2873.5529759975.1147.517764 9995.393.86578710035.947.24558310127.181.213166
 10238.73.18300110421.180.87354511534.470.51556812352.210.80030512444.354.174828
 12472.52.16038412593.449.98023812743.81 25.024912778.3631.1424212874.1736.10293
#Mann= 3 , 0 , 0
7304.247  0.0778       07304.247  0.0778       012874.17  0.0778       0
#XS Ineff= 2 , 0
       09929.384        11550.08       0
Bank Sta=7304.247,12874.17
Exp/Cntr=0.3,0.1

Type RM Length L Ch R = 1 ,946.0878,946.087800,946.087800,946.087800
XS GIS Cut Line= 2
  918469.8766282791427.692855578912165.883989978 788718.20141928
#Sta/Elev= 30
6227.06594.40273 6297.6872.764716373.87253.217046482.71729.964916504.48728.37121
6580.67815.826926689.5244.4239746787.4851.54697410564.420.61763310814.772.415763
10836.530.93298310978.032.32301811086.880.85095911130.422.95040711173.961.031646
11805.260.41499112033.16 2.3911812142.681.24636312164.454.12930112186.221.967434
12316.830.52073112590.2910.5805912686.9123.6734312719.5631.6928912784.8734.18168
12806.6447.2920412871.9464.5615312948.1492.4926213013.44118.791213088.67153.0968
#Mann= 3 , 0 , 0
6227.065  0.0879       06227.065  0.0879       013088.67  0.0879       0
#XS Ineff= 2 , 0
       09091.328                       0
Bank Sta=6227.065,13088.67
Exp/Cntr=0.3,0.1

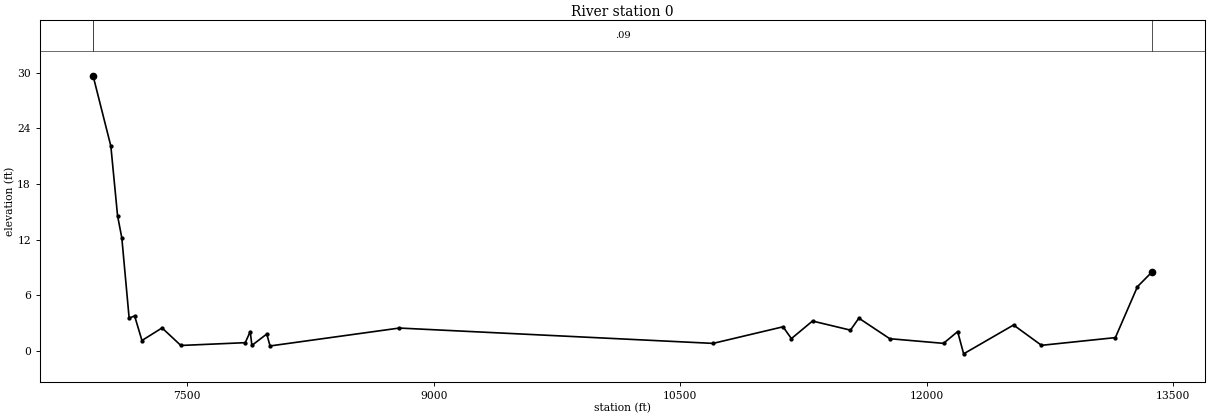
Type RM Length L Ch R = 1 ,       0,0.000000,0.000000,0.000000
XS GIS Cut Line= 6
918742.187325315789950.407323728918330.956965504789749.573892192
915916.963842743789439.824766636914664.334636012788827.125698127
914236.963893945788484.173868073913323.204452719787159.222678295
#Sta/Elev= 30
 6927.2929.670737035.44822.079757076.337 14.56267102.22112.174927146.7363.519695
7180.1233.7527897224.6381.1028427347.0552.4605317461.309 0.567837853.4190.868761
7883.5812.0666957893.6360.5741047984.1221.8003738004.2310.5149288790.8412.446514
10699.630.79162411125.672.58232511176.581.30803211305.013.204529 11535.82.221963
11587.093.51364311775.221.29730412102.190.79517712188.232.06485612224.67-0.33596
12528.362.77538512698.430.58303213147.891.41504813282.336.91370113373.56 8.54735
#Mann= 3 , 0 , 0
 6927.29    0.09       0 6927.29    0.09       013373.56    0.09       0
#XS Ineff= 2 , 0
       08569.118                       0
Bank Sta=6927.29,13373.56
Exp/Cntr=0.3,0.1